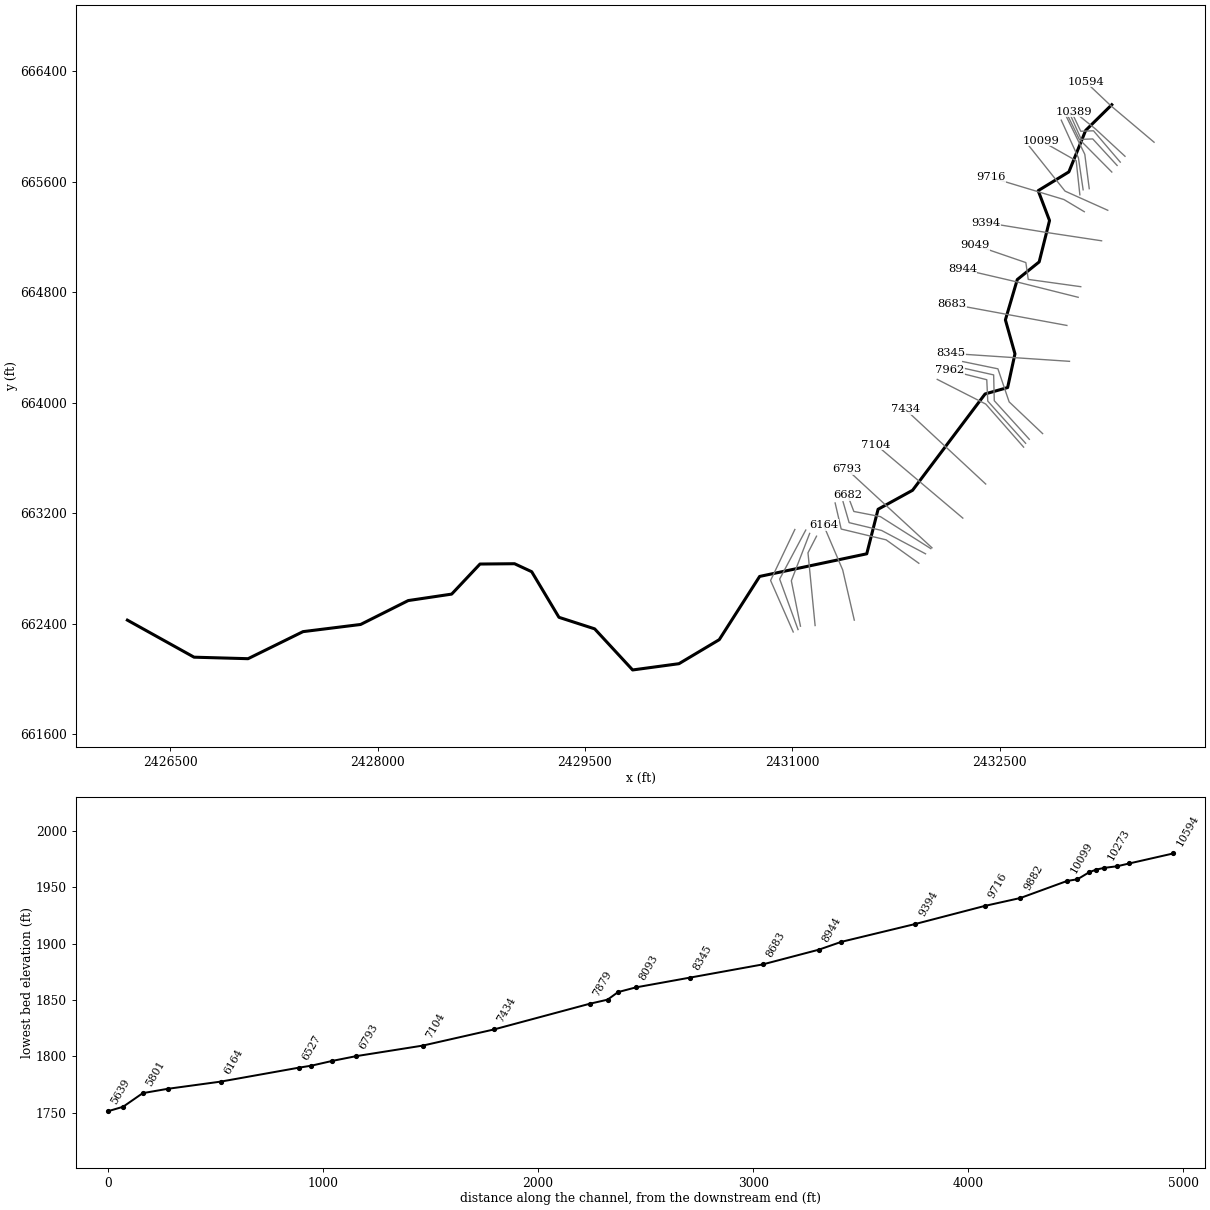
--- NFSBPOTMC_T1.prj (project) ---

Proj Title=NFSBPOTMC_T1
Current Plan=p01
Default Exp/Contr=0,0
English Units
Geom File=g01
Flow File=f01
Plan File=p01
BEGIN DESCRIPTION:
Stream Name: North Fork South Branch Potomac River Tributary 1
Flood Zone: Approximate
Pendleton County, West Virginia
HEC-RAS Version: 5.0.7
Hydrology Method:
Regression equation
END DESCRIPTION:
DSS Export Rating Curves= 0
DSS Export Rating Curve Sorted= 0
DSS Export Volume Flow Curves= 0
DXF OffsetX= 0
DXF OffsetY= 0
DXF ScaleX= 0
DXF ScaleY= 0

--- NFSBPOTMC_T1.p01 (plan) ---

Plan Title=Floodplain
Program Version=5.07
Short Identifier=Floodplain
Geom File=g01
Flow File=f01
Subcritical Flow
K Sum by GR= 0
Std Step Tol= 0.01
Critical Tol= 0.01
Num of Std Step Trials= 20
Max Error Tol= 0.3
Flow Tol Ratio= 0.001
Split Flow NTrial= 30
Split Flow Tol= 0.02
Split Flow Ratio= 0.02
Log Output Level= 0
Friction Slope Method= 1
Unsteady Friction Slope Method= 2
Unsteady Bridges Friction Slope Method= 1
Parabolic Critical Depth
Global Vel Dist= 0 , 0 , 0
Global Log Level= 0
CheckData=False
Encroach Param=-1 ,0,0, 0
Mapping Interval=1HOUR
Computation Time Step Use Courant=        0
Computation Time Step Use Time Series=    0
Computation Time Step Count To Double=0
Computation Time Step Max Doubling=0
Computation Time Step Max Halving=0
Computation Time Step Residence Courant=0
Run HTab= 0
Run UNet= 0
Run Sediment= 0
Run PostProcess= 0
Run WQNet= 0
Run RASMapper= 0
UNET Theta= 0
UNET Theta Warmup= 0
UNET ZTol= 0
UNET ZSATol= 0
UNET MxIter= 0
UNET Max Iter WO Improvement= 0
UNET MaxInSteps= 0
UNET DtIC= 0
UNET DtMin= 0
UNET MaxCRTS= 0
UNET WFStab= 0
UNET SFStab= 0
UNET WFX= 1
UNET SFX= 1
UNET 1D Methodology=Finite Difference
UNET DSS MLevel= 1
UNET Pardiso=0
UNET DZMax Abort= 0
UNET Use Existing IB Tables= 0
UNET Froude Reduction=False
UNET Froude Limit= 0
UNET Froude Power= 0
UNET D1 Cores= 0
UNET D2 Coriolis=0
UNET D2 Cores= 0
UNET D2 Theta= 1
UNET D2 Theta Warmup= 1
UNET D2 Z Tol= 0.01
UNET D2 Volume Tol= 0.01
UNET D2 Max Iterations= 20
UNET D2 Equation= 0
UNET D2 RampUpFraction=0.1
UNET D2 TimeSlices= 1
UNET D2 BCVolumeCheck=0
UNET D1D2 MaxIter= 0
UNET D1D2 ZTol=0.01
UNET D1D2 QTol=0.1
UNET D1D2 MinQTol=1
Write IC File= 0
Write IC File at Fixed DateTime=0
Write IC File at Sim End=0
Echo Input=False
Echo Parameters=False
Echo Output=False
Write Detailed= 0
HDF Write Warmup=0
HDF Write Time Slices=0
HDF Flush=0
HDF Face Node Velocities=0
HDF Compression= 1
HDF Chunk Size= 1
HDF Spatial Parts= 1
HDF Use Max Rows=0
HDF Fixed Rows= 1
Calibration Method= 0
Calibration Iterations= 20
Calibration Max Change=0.05
Calibration Tolerance=0.2
Calibration Maximum=1.5
Calibration Minimum=0.5
Calibration Optimization Method= 1
WQ AD Non Conservative
WQ ULTIMATE=-1
WQ Max Comp Step=1HOUR
WQ Output Interval=15MIN
WQ Output Selected Increments= 0
WQ Output face flow=0
WQ Output face velocity=0
WQ Output face area=0
WQ Output face dispersion=0
WQ Output cell volume=0
WQ Output cell surface area=0
WQ Output cell continuity=0
WQ Output cumulative cell continuity=0
WQ Output face conc=0
WQ Output face dconc_dx=0
WQ Output face courant=0
WQ Output face peclet=0
WQ Output face adv mass=0
WQ Output face disp mass=0
WQ Output cell mass=0
WQ Output cell source sink temp=0
WQ Output nsm pathways=0
WQ Output nsm derived pathways=0
WQ Output MaxMinRange=-1
WQ Daily Max Min Mean=-1
WQ Daily Range=0
WQ Daily Time=0
WQ Create Restart=0
WQ Fixed Restart=0
WQ System Summary=0
WQ Write To DSS=0
WQ Use Fixed Temperature=0
Sorting and Armoring Iterations= 10
XS Update Threshold= 0.02
Bed Roughness Predictor= 0
Hydraulics Update Threshold= 0.02
Energy Slope Method= 1
Volume Change Method= 1
Sediment Retention Method= 0
XS Weighting Method= 0
Number of US Weighted Cross Sections= 1
Number of DS Weighted Cross Sections= 1
Upstream XS Weight=0
Main XS Weight=1
Downstream XS Weight=0
Number of DS XS's Weighted with US Boundary= 1
Upstream Boundary Weight= 1
Weight of XSs Associated with US Boundary= 0
Number of US XS's Weighted with DS Boundary= 1
Downstream Boundary Weight= 0.5
Weight of XSs Associated with DS Boundary= 0.5
Percentile Method= 0
Sediment Output Level= 3
Mass or Volume Output= 0
Output Increment Type= 1
Profile and TS Output Increment= 1
XS Output Flag= 0
XS Output Increment= 10
Write Gradation File= 0
Read Gradation Hotstart= 0
Write HDF5 File= 1
Write Binary Output= 1
Write DSS Sediment File= 0
SV Curve= 0
Specific Gage Flag= 0

--- NFSBPOTMC_T1.f01 (steady flow) ---

Flow Title=Flows
Program Version=5.07
Number of Profiles= 6
Profile Names=P100yr,P10yr,P25yr,P50yr,P500yr,P101yr
River Rch & RM=NFSBPOTMC_T1,Main            ,10594
     327     154     217     271     477     398
River Rch & RM=NFSBPOTMC_T1,Main            ,9882
     632     295     418     522     928     770
River Rch & RM=NFSBPOTMC_T1,Main            ,6793
     806     375     531     665    1186     981
River Rch & RM=NFSBPOTMC_T1,Main            ,4335
    1455     671     955    1198    2154    1771
Boundary for River Rch & Prof#=NFSBPOTMC_T1,Main            , 1
Up Type= 0
Dn Type= 3
Dn Slope=0.01698
Boundary for River Rch & Prof#=NFSBPOTMC_T1,Main            , 2
Up Type= 0
Dn Type= 3
Dn Slope=0.01698
Boundary for River Rch & Prof#=NFSBPOTMC_T1,Main            , 3
Up Type= 0
Dn Type= 3
Dn Slope=0.01698
Boundary for River Rch & Prof#=NFSBPOTMC_T1,Main            , 4
Up Type= 0
Dn Type= 3
Dn Slope=0.01698
Boundary for River Rch & Prof#=NFSBPOTMC_T1,Main            , 5
Up Type= 0
Dn Type= 3
Dn Slope=0.01698
Boundary for River Rch & Prof#=NFSBPOTMC_T1,Main            , 6
Up Type= 0
Dn Type= 3
Dn Slope=0.01698
DSS Import GetInterval= 0
DSS Import GetPeak= 0
DSS Import FillOption= 0

--- NFSBPOTMC_T1.g01 (geometry) ---

Geom Title=Geometry
Program Version=5.07

River Reach=NFSBPOTMC_T1    ,Main
Reach XY= 30
2433312.42162573666157.2368801532433123.19168928 665970.92885381
2433001.95997635665670.9796505872432779.77997448 665535.01043433
2432861.90448223665318.5020090642432787.00436954665019.163040876
2432628.56308536664891.392299026 2432542.6105013664599.376806915
2432611.77342071664353.5990832452432558.69905183664109.340057328
2432395.72792108664063.1095067412431871.04885237663365.760507748
2431621.44108388663228.1469378172431539.42812449662905.678750739
2430764.39752238662741.8027661892430472.24817225662284.002172589
2430180.61555347662109.976602018 2429845.3859089662064.630892187
2429570.59479186662362.2999162522429312.28330061662445.809263662
2429115.09767139662775.9831439852428990.88991448662833.878041312
 2428741.0180389662831.5443845842428536.07553548662613.845344886
2428221.70313264662567.056396499 2427877.2504095662393.990469679
2427460.52289656662342.1191823332427062.81667092662146.210453391
 2426672.0625312662157.1326756632426189.64152244662425.447472081

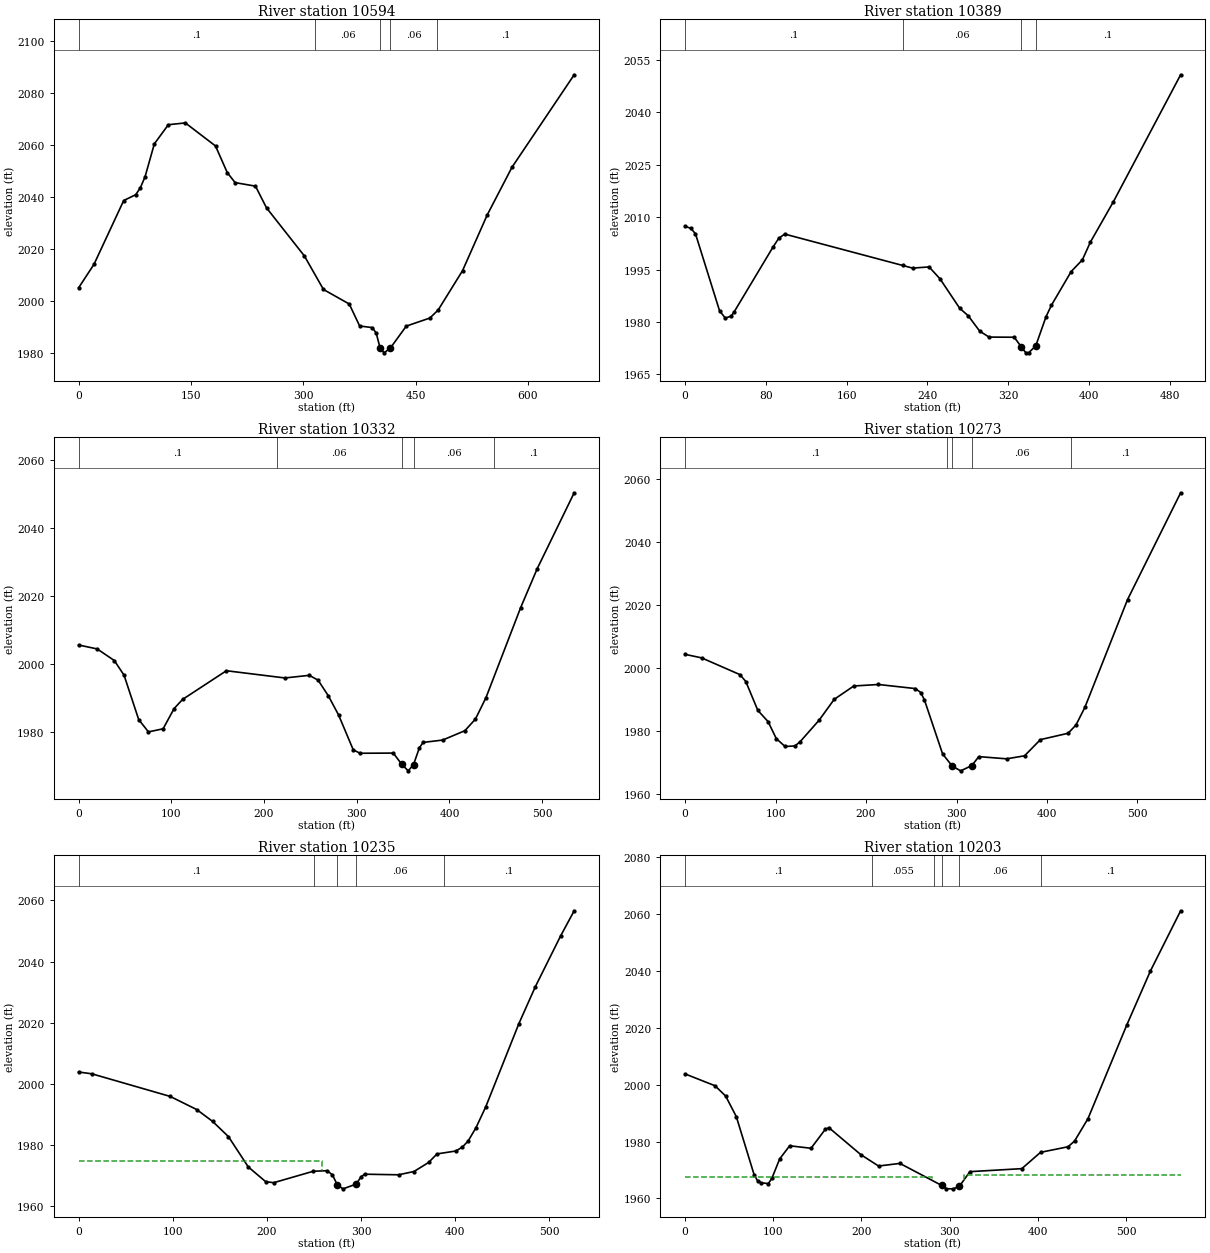
Type RM Length L Ch R = 1 ,10594   ,204.2,204.5,205
XS GIS Cut Line= 3
     2433618.402       665885.68     2433305.969      666149.598
2433122.55196846666323.562017641
#Sta/Elev= 30
       0 2005.06    20.5 2014.07    60.2 2038.62    76.3 2040.87    82.5 2043.57
    88.7 2047.75   101.1 2060.42   119.8 2067.79   142.5 2068.48   182.8 2059.61
   198.5 2049.36     209 2045.51   236.2 2044.15   250.9 2035.81   301.5  2017.3
     327 2004.39   361.4 1998.81   375.3 1990.35   392.4 1989.73   397.5 1987.53
   402.7 1981.77     408 1980.02   416.51981.933   437.6 1990.31     469  1993.4
   480.1 1996.47   512.7 2011.63   545.7 2033.09   578.8 2051.45   661.8    2087
#Mann= 5 ,-1 , 0
       0      .1       0  316.13     .06       0   402.7    .045       0
   416.5     .06       0  478.07      .1       0
Bank Sta=402.7,416.5
XS Rating Curve= 0 ,0
Exp/Cntr=0.3,0.1

Type RM Length L Ch R = 1 ,10389   ,52.5,57.5,61.5
XS GIS Cut Line= 3
2433408.02426876665783.9231326922433194.86110034665981.347237637
2433038.94589188666106.866712458
#Sta/Elev= 30
       0 2007.42     5.8 2006.77    10.3 2005.24    34.1 1983.21    39.8  1981.1
    45.6 1981.67    48.3 1982.75    86.8 2001.33    92.7 2003.94    98.6 2005.17
   215.3 1996.19   225.3 1995.42   241.6 1995.76   252.5 1992.32   271.9 1983.92
   280.4 1981.76   291.7 1977.37     301 1975.66   325.9 1975.62   332.9 1972.88
   337.2 1971.23   340.1 1971.15   347.2 1973.13   357.4 1981.49   362.8 1984.81
   382.3 1994.43   393.4 1997.79   401.4  2002.9   424.2 2014.48   490.7 2050.79
#Mann= 4 ,-1 , 0
       0      .1       0   215.3     .06       0   332.9    .045       0
   347.2      .1       0
Bank Sta=332.9,347.2
XS Rating Curve= 0 ,0
Exp/Cntr=0.5,0.3

Type RM Length L Ch R = 1 ,10332   ,59.4,58.8,58.9
XS GIS Cut Line= 4
2433373.62799466665741.6375818552433180.02255559665968.435481446
2433087.53382109 665965.201609612433026.09025621666095.203257411
#Sta/Elev= 30
       0 2005.56      20 2004.41    38.5    2001      49  1996.7    64.8 1983.67
    75.3 1980.06    91.1 1980.97     103 1986.91   112.1 1989.59   159.4 1998.01
   222.5 1995.89   248.8 1996.66   258.3 1995.24   269.4 1990.62   280.4 1985.02
   296.2  1974.8   303.5 1973.79   339.4 1973.84   348.51970.559   355.5 1968.63
   361.21970.456   367.5 1975.35   371.5 1976.97   392.6 1977.66   416.6 1980.41
     428 1983.82   439.4 1990.13   476.8 2016.55   494.7    2028   534.5 2050.24
#Mann= 5 ,-1 , 0
       0      .1       0  213.86     .06       0   348.5    .045       0
   361.2     .06       0  447.64      .1       0
#XS Ineff= 2 , 0
          339.43  1973.7   365.3          1973.3
Permanent Ineff=
       F       F
Bank Sta=348.5,361.2
XS Rating Curve= 0 ,0
Exp/Cntr=0.5,0.3

Type RM Length L Ch R = 1 ,10273   ,48.8,38.1,31.8
XS GIS Cut Line= 4
2433350.89925816665717.4764078052433174.59796417 665909.52099354
2433091.41446729665906.3451421982433008.52076378666092.520422588
#Sta/Elev= 30
       0 2004.25    18.2 2003.14    60.6 1997.81    67.1 1995.62    80.4 1986.43
    91.7 1982.88   100.8 1977.46   110.5 1974.96   121.4 1975.14   126.8 1976.38
   148.1 1983.31   164.8 1989.95   186.5  1994.2   213.7 1994.67   254.6 1993.37
   260.5  1992.1   264.6  1989.7   284.6 1972.61   295.3 1968.71   304.6 1967.22
   316.91968.892   324.6 1971.74   355.4 1971.04   375.2    1972   392.7 1977.14
   423.4 1979.17   432.1 1981.83   441.8 1987.36     489 2021.66   547.7 2055.62
#Mann= 5 ,-1 , 0
       0      .1       0  289.03     .06       0   295.3    .045       0
   316.9     .06       0  426.98      .1       0
Bank Sta=295.3,316.9
XS Rating Curve= 0 ,0
Exp/Cntr=0.5,0.3

Type RM Length L Ch R = 1 ,10235   ,36.6,32.3,30.6
XS GIS Cut Line= 3
2433312.58057908665669.8711695122433077.15470943665907.237362263
 2432993.0740417666079.926118297
#Sta/Elev= 30
       0 2003.89      14  2003.3    97.2 1995.91   125.4 1991.62   142.3 1987.74
   159.2 1982.74   180.2 1972.85   198.6 1968.06   207.1 1967.69   249.3 1971.44
   263.9 1971.62   269.6 1970.28   274.81966.968   280.9 1965.69   294.71967.228
     300  1969.6   303.7 1970.48   339.8 1970.28   356.2 1971.35   371.8 1974.32
   380.7 1977.11   400.7 1978.06   407.7 1979.36   413.7  1981.3   422.1 1985.67
   432.4 1992.45   467.7 2019.73   485.2 2031.81   511.9 2048.32   526.4  2056.6
#Mann= 5 ,-1 , 0
       0      .1       0  250.17     .06       0   274.8    .045       0
   294.7     .06       0  388.59      .1       0
#XS Ineff= 2 , 0
          258.22 1974.77
Permanent Ineff=
       F       F
Bank Sta=274.8,294.7
XS Rating Curve= 0 ,0
Exp/Cntr=0.5,0.3

Type RM Length L Ch R = 1 ,10203   ,53.5,55.1,54.6
XS GIS Cut Line= 3
2433149.29465778665549.2894356182433117.06010019665798.233443327
2432980.64151109666077.652019322
#Sta/Elev= 30
       0 2003.79    33.9 1999.64      46 1996.01    58.1 1988.77    78.2 1968.43
    82.3 1966.14    86.3 1965.51    94.4 1965.24    98.4 1967.07   107.3 1973.93
   118.6 1978.53   142.8 1977.65   158.9 1984.28     163 1984.92   199.3 1975.41
   219.4 1971.41   243.6 1972.33   290.9 1964.61   296.3 1963.42   304.1 1963.39
     311 1964.25     323 1969.43   381.9 1970.49   403.1 1976.22   434.3 1978.18
   441.7 1980.19   456.9 1988.06     501 2021.05   527.7 2039.97     562 2061.15
#Mann= 6 ,-1 , 0
       0      .1       0  211.73    .055       0   281.9     .06       0
   290.9    .045       0     311     .06       0  403.74      .1       0
#XS Ineff= 2 , 0
          280.57  1967.6  316.45          1968.2
Permanent Ineff=
       F       F
Bank Sta=290.9,311
XS Rating Curve= 0 ,0
Exp/Cntr=0.5,0.3

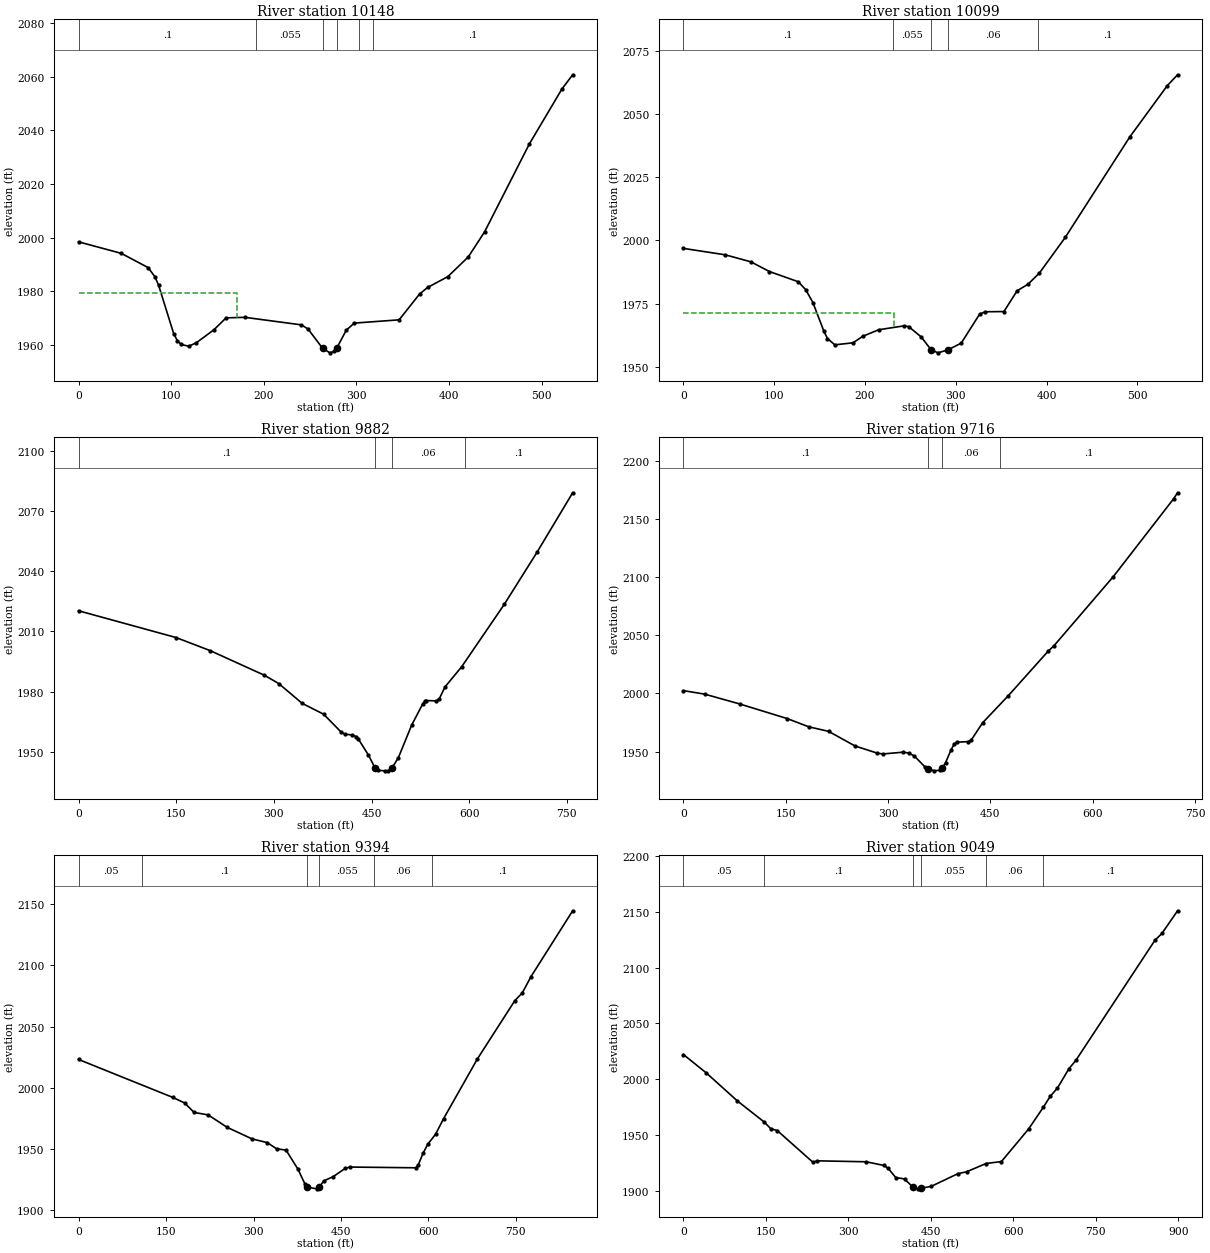
Type RM Length L Ch R = 1 ,10148   ,44.1,48.8,54
XS GIS Cut Line= 3
 2433105.0519496665541.2927028482433070.88775172665772.805067825
2432946.74164471666045.428039487
#Sta/Elev= 30
       0 1998.45    46.1 1994.16    75.1 1988.86    82.5 1985.42    86.5 1982.21
   102.7 1964.28   106.7 1961.64   110.8 1960.22   118.9 1959.56     127  1960.8
   146.2 1965.69   159.3 1970.12   179.6 1970.32   240.7 1967.51   247.8 1965.97
   263.71958.712   271.5 1957.09   275.9 1957.61   279.1 1959.01   289.1 1965.53
   297.8 1968.17   346.2 1969.39   368.2 1978.98     377 1981.46   398.8 1985.49
   420.9 1992.84   438.5 2002.18   486.8 2034.91     522  2055.4   533.6  2060.7
#Mann= 6 ,-1 , 0
       0      .1       0  192.16    .055       0   263.7    .045       0
   279.1    .055       0  302.89     .06       0  318.01      .1       0
#XS Ineff= 2 , 0
          171.25 1979.29
Permanent Ineff=
       F       F
Bank Sta=263.7,279.1
XS Rating Curve= 0 ,0
Exp/Cntr=0.5,0.3

Type RM Length L Ch R = 1 ,10099   ,217.9,216.3,210.6
XS GIS Cut Line= 3
 2433081.4417007665505.0835259192433054.62284286665751.862730106
2432796.95778331665897.982310724
#Sta/Elev= 30
       0 1996.84    46.1  1994.3    74.2 1991.54    94.8 1987.68   126.5 1983.67
   134.6 1980.57   142.6 1975.46   154.7 1964.13   158.7 1961.21   166.8 1958.73
   186.9 1959.54   197.6 1962.11   215.1 1964.69   243.2 1966.24   248.2 1965.93
   261.9 1961.87   272.71956.871   280.3 1955.57   291.4 1956.73   306.1 1959.43
   326.3 1970.85   332.5  1971.8   353.1 1971.88   367.7 1980.12   379.5 1982.64
   392.2  1987.1   420.6 2001.15   491.8  2040.9   533.2  2061.2   544.4 2065.44
#Mann= 5 ,-1 , 0
       0      .1       0  230.84    .055       0   272.7    .045       0
   291.4     .06       0   390.3      .1       0
#XS Ineff= 2 , 0
          231.53  1971.2
Permanent Ineff=
       F       F
Bank Sta=272.7,291.4
XS Rating Curve= 0 ,0
Exp/Cntr=0.3,0.1

Type RM Length L Ch R = 1 ,9882    ,160.3,166,171.5
XS GIS Cut Line= 3
2433283.25120809665392.9621470582432974.12772026665531.702610099
2432712.46807505665860.298443618
#Sta/Elev= 30
       0  2020.3   149.6 2006.97   202.2 2000.43   285.5 1988.14   307.5    1984
   343.5 1974.13   376.4 1968.74   403.3 1959.82     409 1958.78   420.4 1958.39
   426.1  1957.6   429.8 1956.33   445.2 1948.37   455.4  1941.9   460.5 1940.72
   470.7  1940.5   475.9 1940.61     481 1941.71   491.2 1947.05   511.6 1963.29
   528.5  1973.8   531.4 1975.07   534.2 1975.54   549.7 1975.38   554.2 1976.53
   562.7 1982.29   588.3 1992.34   653.8 2023.47   703.9 2049.36   758.9 2079.13
#Mann= 4 ,-1 , 0
       0      .1       0   455.4    .045       0     481     .06       0
  593.25      .1       0
Bank Sta=455.4,481
XS Rating Curve= 0 ,0
Exp/Cntr(USF)=0,0
Exp/Cntr=0.3,0.1

Type RM Length L Ch R = 1 ,9716    ,321.6,322.5,324.5
XS GIS Cut Line= 3
2433113.47407622665382.6119375732432965.79796772665470.875007615
2432437.15545442665630.779308268
#Sta/Elev= 30
       0 2002.42    31.1 1999.41    82.4 1990.97   152.3 1978.35   183.6 1971.33
   212.8 1967.39   251.5 1954.84   283.9 1948.71   292.2 1947.97   321.5 1949.47
   329.9 1948.81   338.4 1946.21   354.2 1936.78   359.1 1935.17   367.5 1933.46
   375.8 1934.02   379.3 1935.71   384.2 1940.44   392.5 1951.78   396.7  1956.2
   400.9 1958.08   417.6  1958.6   421.8 1959.88   438.5 1974.76   476.1    1998
   534.6 2036.33     543 2040.91   630.1 2100.43   718.5 2167.36   724.3 2172.52
#Mann= 4 ,-1 , 0
       0      .1       0   359.1    .045       0   379.3     .06       0
  463.74      .1       0
Bank Sta=359.1,379.3
XS Rating Curve= 0 ,0
Exp/Cntr=0.3,0.1

Type RM Length L Ch R = 1 ,9394    ,355.6,344.7,335.5
XS GIS Cut Line= 3
2433238.56662084665171.991104201     2432838.937       665232.49
2432401.60481881665303.619825761
#Sta/Elev= 30
       0 2023.15   161.6 1992.15   181.9 1987.61   198.1  1979.9   222.3 1977.84
   254.7 1967.73   297.5 1958.24   323.5 1955.26   339.6 1950.18   355.8  1949.1
   376.1 1933.61   388.2 1921.47     392 1918.89   408.4 1917.46   412.5 1918.83
   420.6 1923.98   436.8 1927.48   457.1 1934.12   465.2 1935.26   578.6 1934.65
   582.7 1937.28   590.8 1946.59   598.9 1953.96   612.1 1961.99     626 1974.84
     684 2023.66     748 2071.12     761 2077.62   775.9  2090.9   847.3 2144.62
#Mann= 6 ,-1 , 0
       0     .05       0  109.64      .1       0     392    .045       0
   412.5    .055       0  506.92     .06       0  606.23      .1       0
Bank Sta=392,412.5
XS Rating Curve= 0 ,0
Exp/Cntr=0.3,0.1

Type RM Length L Ch R = 1 ,9049    ,96.1,105.3,112.5
XS GIS Cut Line= 4
2433087.91279464664839.7276804992432707.86887546664892.543451744
2432690.64634136665014.2493593952432319.78777371665141.696111747
#Sta/Elev= 30
       0 2022.11    41.6 2005.58    98.1 1980.48   146.6 1961.67   158.7 1955.66
   170.8 1953.83   235.4 1925.48   243.5 1926.73   332.3 1925.88   364.6  1922.6
   372.6  1919.9   386.1 1911.72   402.2 1910.48   417.61902.988   426.5  1901.6
   432.2 1902.16   450.7 1903.81   499.2 1915.21     515  1916.9   550.5 1924.33
   578.4 1926.08   627.9 1955.34   654.5  1974.7   667.2 1984.63   680.2 1991.97
   701.1  2009.3   713.8 2016.88   857.6 2124.58   870.3 2130.72   898.8 2151.09
#Mann= 6 ,-1 , 0
       0     .05       0   146.6      .1       0   417.6    .045       0
   432.2    .055       0   550.5     .06       0   654.5      .1       0
Bank Sta=417.6,432.2
XS Rating Curve= 0 ,0
Exp/Cntr(USF)=0,0
Exp/Cntr=0.3,0.1

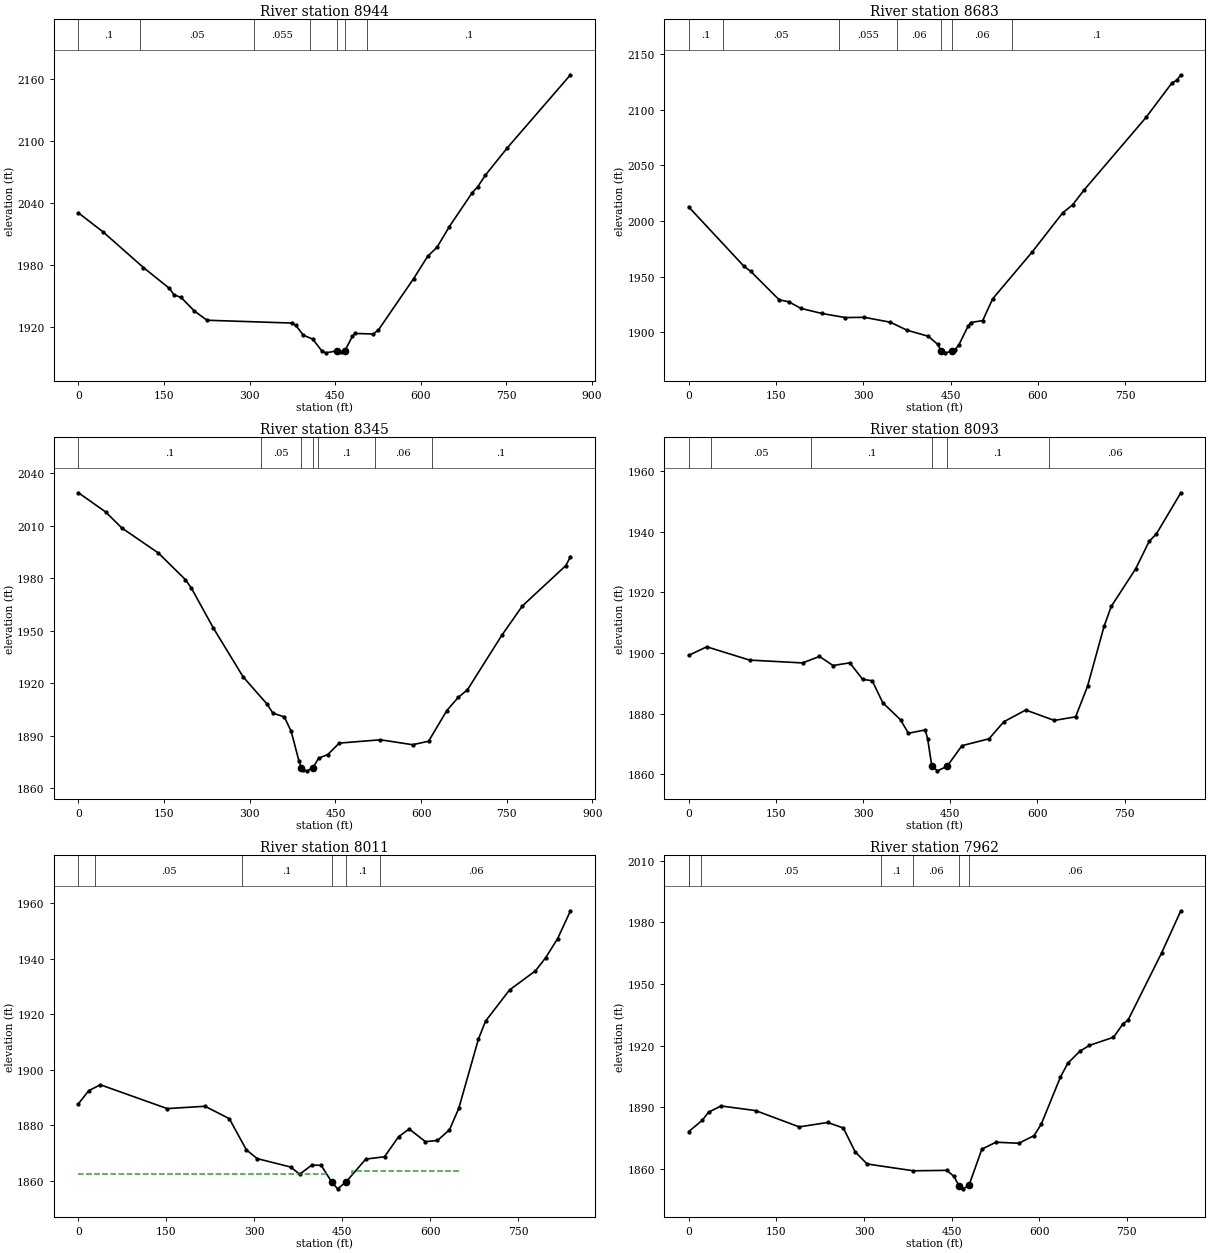
Type RM Length L Ch R = 1 ,8944    ,259.1,260.6,260.6
XS GIS Cut Line= 3
2433069.24645442664762.961881344     2432622.255      664875.035
     2432231.008      664966.261
#Sta/Elev= 30
       0 2030.43    43.8  2011.7   113.9  1977.4   159.3 1957.23   167.5 1950.98
   179.9 1948.38   203.1 1935.28   225.3 1926.25   373.7 1923.53   381.2 1921.15
   394.3 1911.72   410.8 1907.95   427.3 1895.97   433.9 1894.61   453.6 1896.58
   460.4 1895.06     467 1896.62   480.3  1910.7     485 1913.42   516.9  1912.9
     526 1916.92   587.7 1966.76   612.3 1988.36   628.7 1997.16   650.1 2017.02
   690.1 2049.92   700.1 2055.91   713.4 2067.09   751.9 2093.65   862.6 2164.51
#Mann= 7 ,-1 , 0
       0      .1       0  107.66     .05       0  307.01    .055       0
  406.69     .06       0   453.6    .045       0     467     .06       0
   506.3      .1       0
Bank Sta=453.6,467
XS Rating Curve= 0 ,0
Exp/Cntr=0.3,0.1

Type RM Length L Ch R = 1 ,8683    ,337,338.8,338.4
XS GIS Cut Line= 2
     2432987.542      664559.107     2432155.926      664712.579
#Sta/Elev= 30
       0 2012.61    94.4  1959.6   106.6 1954.72   155.4 1929.18   171.6 1927.52
   192.8  1921.5   228.6 1916.95   269.3 1913.25   301.8 1913.48   346.6 1909.06
     375 1901.92   411.6 1896.47   427.9 1889.19   433.2 1883.47     440 1881.57
   452.3 1882.99   457.2 1884.24   464.1 1888.61   480.1 1905.59   484.8 1908.81
   505.2 1910.55   522.4 1930.18   589.9 1971.95   642.6 2007.32   659.8 2014.55
   679.6 2027.98   785.8    2093   830.6 2124.18   838.7 2126.35   845.7 2131.38
#Mann= 7 ,-1 , 0
       0      .1       0   59.26     .05       0  257.94    .055       0
  357.28     .06       0   433.2    .045       0   452.3     .06       0
  555.96      .1       0
Bank Sta=433.2,452.3
XS Rating Curve= 0 ,0
Exp/Cntr=0.3,0.1

Type RM Length L Ch R = 1 ,8345    ,259.6,251.3,230.8
XS GIS Cut Line= 2
     2433006.343      664299.2582432146.71949445664356.730527731
#Sta/Elev= 30
       0 2028.81    47.7 2017.83    75.8 2008.73   139.9 1994.39   187.2 1979.19
   197.6 1974.38   236.1 1951.55   288.2 1923.63   330.8 1907.79   340.4  1902.8
   360.4 1900.73   372.4 1892.49   386.3 1875.22   390.1 1871.75   392.5 1870.37
   400.5 1869.86   410.61871.676   420.5 1877.07   436.6 1879.18   456.6 1885.71
   528.8 1887.61   584.9  1884.8     613 1886.77     645 1904.35   665.1  1911.9
   681.1  1916.2   741.2 1947.31   777.3 1964.13   853.5 1987.23   861.5 1992.38
#Mann= 7 ,-1 , 0
       0      .1       0  319.43     .05       0   390.1    .045       0
   410.6     .05       0  419.19      .1       0  518.95     .06       0
   618.7      .1       0
Bank Sta=390.1,410.6
XS Rating Curve= 0 ,0
Exp/Cntr=0.3,0.1

Type RM Length L Ch R = 1 ,8093    ,84.4,82.2,76.8
XS GIS Cut Line= 4
2432811.81772849663776.1262896922432569.53640631 664005.89298985
2432488.42252251664245.0230299812432233.52308197664297.615787154
#Sta/Elev= 30
       0 1899.28      31 1902.09   104.6 1897.71   195.8 1896.77   224.9 1898.91
   248.2 1895.92   277.1  1896.8   299.2 1891.36   315.7 1890.89   333.9 1883.63
   364.5 1878.01   377.9 1873.58   406.8 1874.69     411 1871.83   418.21862.842
   427.9  1861.2   444.41862.679   470.1 1869.49   516.7 1871.77   541.9 1877.35
   579.9 1881.25     629 1877.82   665.7 1879.01   686.2 1889.08   714.7 1908.88
     727  1915.4   768.9 1927.76   792.3 1936.87   804.6 1939.28   846.7 1952.86
#Mann= 6 ,-1 , 0
       0      .1       0   38.79     .05       0  210.34      .1       0
   418.2    .045       0   444.4      .1       0  620.24     .06       0
Bank Sta=418.2,444.4
XS Rating Curve= 0 ,0
Exp/Cntr=0.5,0.3

Type RM Length L Ch R = 1 ,8011    ,48.6,48.8,50.2
XS GIS Cut Line= 4
      2432715.53      663734.824 2432462.1242834664014.202938055
2432457.68138644664200.988429657 2432189.3740136664261.047379229
#Sta/Elev= 30
       0 1887.76    17.6 1892.46    37.4 1894.58   151.3 1885.99   215.8 1886.83
   257.2 1882.36   286.3 1871.12   304.8 1867.95   361.9 1864.91   377.2 1862.32
   397.9 1865.62   413.9 1865.52     432 1859.46   441.9 1857.05   456.31859.554
   489.9 1867.78   521.9 1868.62   545.9 1875.86     564 1878.63   591.6 1874.07
   612.1 1874.49   632.6 1878.33   648.5 1886.08   681.9 1910.98   694.1 1917.52
   735.1 1928.79   779.1 1935.64   796.6 1940.38   817.1 1947.31     839 1957.33
#Mann= 6 ,-1 , 0
       0      .1       0   28.11     .05       0  278.62      .1       0
     432    .045       0   456.3      .1       0  514.97     .06       0
#XS Ineff= 2 ,-1
       0  423.98 1862.42  466.13     649  1863.4
Permanent Ineff=
       F       F
Bank Sta=432,456.3
XS Rating Curve= 0 ,0
Exp/Cntr=0.5,0.3

Type RM Length L Ch R = 1 ,7962    ,74.8,83,91.5
XS GIS Cut Line= 4
        2432689.      663705.755  2432415.050517 664011.25965668
2432407.83089551664166.0930860042432138.87397292664234.024437349
#Sta/Elev= 30
       0 1878.22      23 1883.64    33.8  1887.6    55.3 1890.66   114.4  1888.4
   189.1 1880.47   237.9 1882.62   264.8 1879.92     285 1868.31   305.5 1862.42
   384.8 1859.11     442 1859.32     454 1856.42   463.41851.572     470 1850.33
   479.91852.063     502 1869.65   526.1 1873.02   565.3 1872.51   591.2 1876.19
   603.6 1881.71   636.6 1904.78   649.2 1911.41   669.6 1917.27   686.1 1920.11
   727.4 1924.09   743.9 1930.69   752.1 1932.29   809.9 1965.16   842.7 1985.62
#Mann= 7 ,-1 , 0
       0      .1       0     .57      .1       0   20.39     .05       0
  328.47      .1       0  383.46     .06       0   463.4    .045       0
   479.9     .06       0
Bank Sta=463.4,479.9
XS Rating Curve= 0 ,0
Exp/Cntr=0.5,0.3

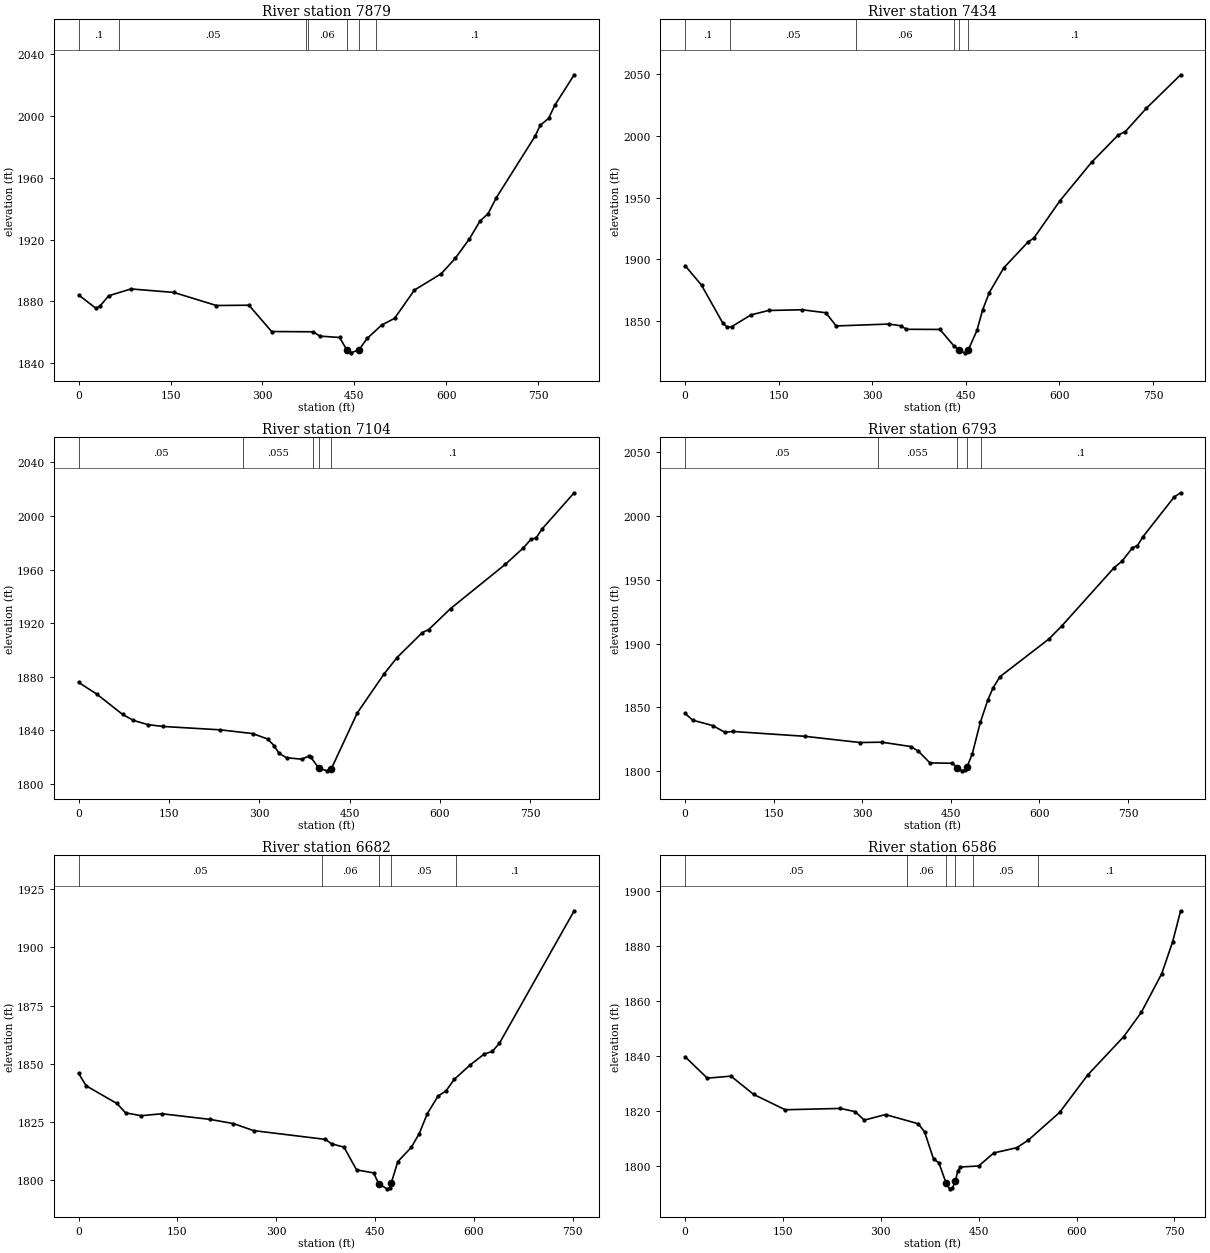
Type RM Length L Ch R = 1 ,7879    ,446.6,445.2,440.7
XS GIS Cut Line= 3
2432674.53803474  663678.09886052432400.63886745663989.668700157
2432049.56458525664168.485738642
#Sta/Elev= 30
       0 1884.19    27.7 1875.72    34.4 1876.77      49 1883.67    85.4 1888.11
   155.5 1885.83   224.7 1877.38     278 1877.56     315 1860.52     383 1860.35
   393.5 1857.56   425.9 1856.66     438 1848.47   443.9 1846.72   457.4 1848.56
   470.8 1856.02   494.5 1864.68   515.7 1869.06     548 1887.34     592 1898.04
   614.5 1907.84   637.9 1920.57   655.1 1932.08   668.4  1936.9   681.8 1947.23
   744.7 1986.85   753.6  1994.2   767.1 1998.55     777 2006.94   808.8 2026.81
#Mann= 7 ,-1 , 0
       0      .1       0   66.26     .05       0  370.69      .1       0
  373.79     .06       0     438    .045       0   457.4     .06       0
  485.86      .1       0
Bank Sta=438,457.4
XS Rating Curve= 0 ,0
Exp/Cntr=0.3,0.1

Type RM Length L Ch R = 1 ,7434    ,330.9,330.5,330.6
XS GIS Cut Line= 2
     2432400.015      663410.9942431818.36743727663951.856423964
#Sta/Elev= 30
       0 1894.77    26.3 1878.91    60.3 1848.22    67.3 1844.85    74.4 1845.09
   105.5 1854.74   133.8 1858.32   187.6 1858.91   225.7 1856.47   242.1 1845.77
   326.3  1847.3   345.8 1845.92   354.6 1843.05   408.4 1842.94     431 1829.52
   438.7 1826.58     448 1823.93   453.7 1826.05   467.8 1842.09   476.9 1858.78
   487.6 1872.88   510.9 1892.99   549.9 1914.06   558.9 1917.02   600.8 1947.37
   651.7 1978.77   694.2 2000.79   705.6 2003.57   739.5 2022.63   794.3 2049.73
#Mann= 6 ,-1 , 0
       0      .1       0   72.49     .05       0  273.82     .06       0
  430.66      .1       0   438.7    .045       0   453.7      .1       0
Bank Sta=438.7,453.7
XS Rating Curve= 0 ,0
Exp/Cntr=0.3,0.1

Type RM Length L Ch R = 1 ,7104    ,312.8,311,310.9
XS GIS Cut Line= 2
     2432234.514      663164.1562431606.14680492663695.328435597
#Sta/Elev= 30
       0 1875.67    30.2 1866.94      73 1851.79      91  1847.3   114.9 1844.16
   140.5 1842.78   235.4 1840.26   289.3 1837.45     314 1833.37   324.4 1828.53
   332.6  1822.8   345.2 1819.42   370.8 1818.33     382 1820.67     385 1820.12
   399.1 1811.42   413.2 1809.64   419.71811.283   462.7 1852.92     507 1881.92
   528.7 1894.26   570.6 1912.89   581.1 1915.08   617.6 1930.86   708.5 1963.89
   738.2 1976.07   751.1 1982.57   759.6 1983.62   769.6 1990.37   822.8 2017.34
#Mann= 5 ,-1 , 0
       0     .05       0  273.44    .055       0  389.31      .1       0
   399.1    .045       0   419.7      .1       0
Bank Sta=399.1,419.7
XS Rating Curve= 0 ,0
Exp/Cntr=0.3,0.1

Type RM Length L Ch R = 1 ,6793    ,104.5,110.9,114.9
XS GIS Cut Line= 2
2432011.36688347662949.2241411772431394.83713993663518.263322144
#Sta/Elev= 30
       0 1845.24    12.9 1839.97    46.9 1835.71    67.3 1830.45    80.9 1831.12
   202.3 1827.34     296 1822.45   332.9 1822.71   381.9 1819.32   395.1 1815.62
   414.5 1806.47   452.6 1806.18   460.31802.815   468.7 1800.24   474.3 1801.05
   477.2 1803.23   486.1 1813.27   499.8 1838.21   512.5 1855.75   521.4  1865.3
   533.2 1874.09   615.8 1903.57   637.7 1913.83   726.3 1959.51   739.7 1964.66
   757.4 1975.16   765.9 1976.84     775 1983.73   828.1 2015.02     839 2018.31
#Mann= 5 ,-1 , 0
       0     .05       0  326.07    .055       0   460.3    .045       0
   477.2    .055       0  501.07      .1       0
Bank Sta=460.3,477.2
XS Rating Curve= 0 ,0
Exp/Cntr=0.5,0.3

Type RM Length L Ch R = 1 ,6682    ,95.6,96.1,95.5
XS GIS Cut Line= 4
2432002.95894312662943.031302389 2431638.1518653663174.802907166
2431445.98903281663212.2370555442431401.95371418663328.565859956
#Sta/Elev= 30
       0 1845.72    11.6 1840.38      58 1832.81    71.3 1828.76      95 1827.53
   126.5 1828.37   199.3 1825.95   235.1 1824.13   265.6 1821.11   374.6 1817.33
   384.1 1815.41   402.9 1813.99     422 1804.18   447.9 1802.89   455.61798.219
   468.3 1796.02   472.4 1796.43   474.91798.722   484.6 1807.75     505 1813.85
   517.2 1819.85   529.4 1828.42   545.7 1835.98   557.9 1838.24   570.2 1843.15
   594.6 1849.44     616 1854.13     628  1855.2   638.8 1858.69   752.4 1915.82
#Mann= 5 ,-1 , 0
       0     .05       0  369.05     .06       0   455.6    .045       0
   474.9     .05       0   572.9      .1       0
#XS Ineff= 2 , 0
          448.68 1802.29  479.47          1801.7
Permanent Ineff=
       F       F
Bank Sta=455.6,474.9
XS Rating Curve= 0 ,0
Exp/Cntr=0.5,0.3

Type RM Length L Ch R = 1 ,6586    ,59.3,58.7,58.7
XS GIS Cut Line= 4
2431964.83689881662905.5651595232431646.68738422  663074.6889223
2431411.89112031663131.2463947892431367.82090445663282.771301283
#Sta/Elev= 30
       0 1839.82    34.1 1832.05    70.3 1832.78   105.1 1826.14   153.4 1820.57
   237.9 1821.05   260.6 1819.89   274.6  1816.8   307.2 1818.83   357.5 1815.47
   367.1 1812.51   380.8  1802.7     389  1801.3   399.9 1794.05   405.5 1791.84
   409.6 1792.01   414.2 1794.62   417.9 1798.18     422 1799.78     450 1800.14
   473.2 1804.87   508.4 1806.78   526.2 1809.55   574.2 1819.63   617.2 1833.22
   672.3 1847.11   699.3 1855.95   730.6 1869.99   747.3 1881.56   759.6 1892.85
#Mann= 6 ,-1 , 0
       0     .05       0  339.62     .06       0   399.9    .045       0
   414.2     .06       0  441.34     .05       0     541      .1       0
Bank Sta=399.9,414.2
XS Rating Curve= 0 ,0
Exp/Cntr=0.5,0.3

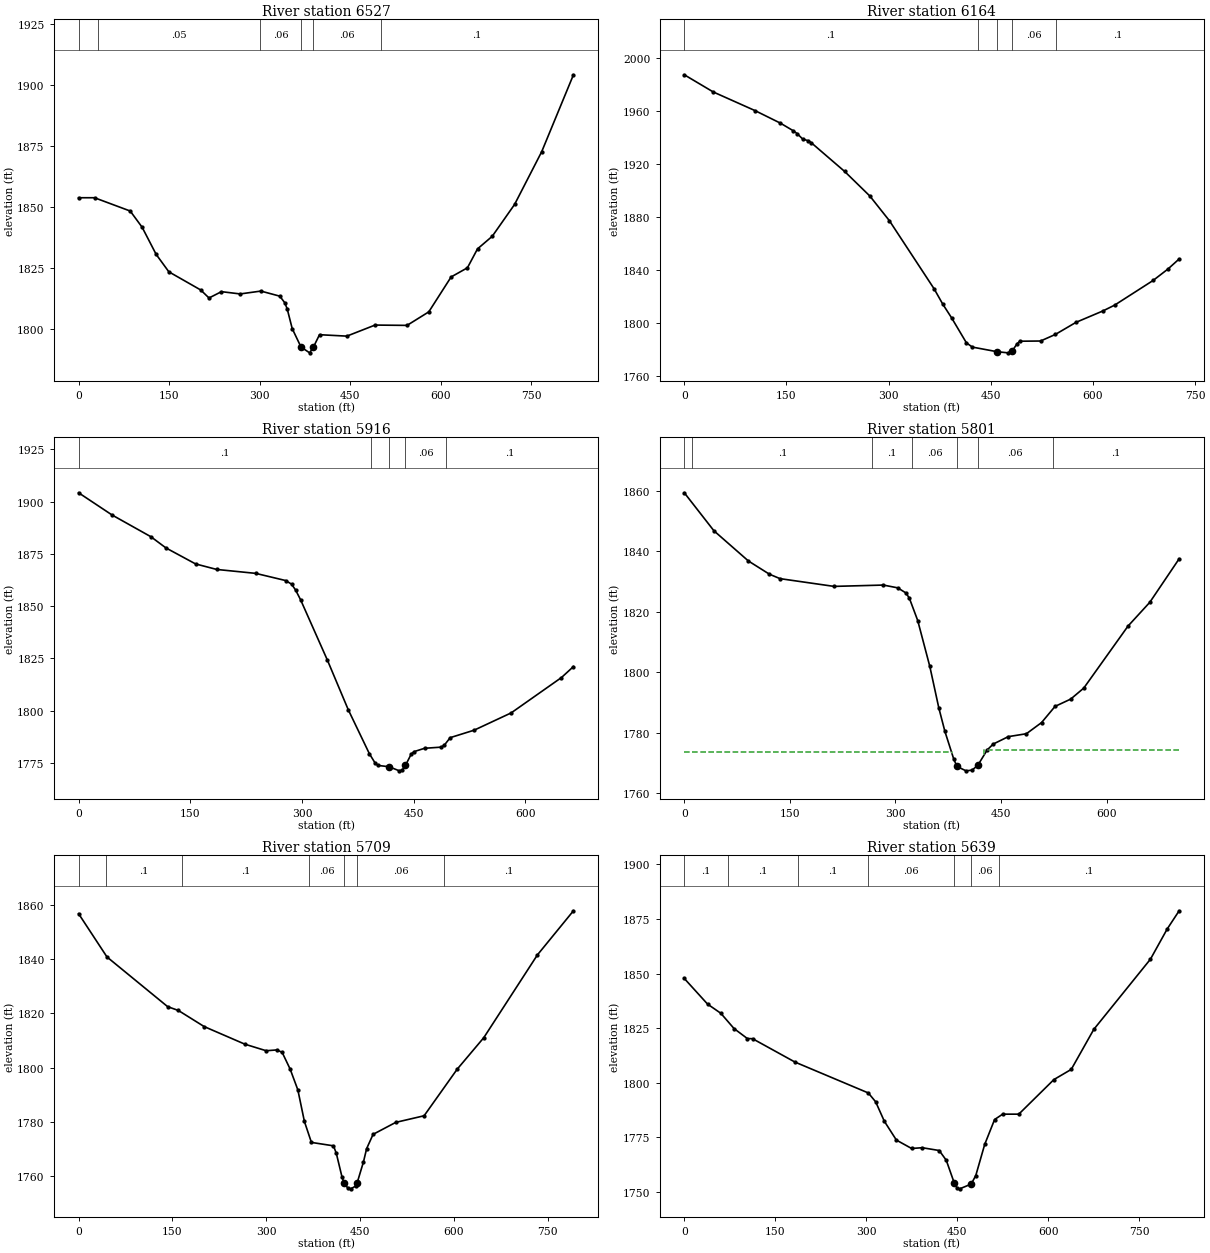
Type RM Length L Ch R = 1 ,6527    ,373.1,362.8,354.5
XS GIS Cut Line= 4
2431916.22455095662837.0786358992431679.42682427663006.810931959
2431354.41178208663084.938182185 2431310.6971136663273.892681576
#Sta/Elev= 30
       0 1853.61    26.4 1853.61    85.5 1848.16   105.2 1841.53   128.5 1830.38
   149.5 1823.25   202.2 1815.82     216 1812.53   236.6 1815.12   267.6 1814.19
   301.9 1815.36   333.2 1813.28   341.4  1810.6   345.5 1808.07   353.8 1799.99
   368.3 1792.46   382.6 1790.05     3891792.439     399 1797.48   444.3  1796.9
     491 1801.43     544  1801.3     580 1806.84     617 1821.15     644  1824.9
   660.7 1832.65   685.1 1837.81   722.1 1850.86     767 1872.47   819.6    1904
#Mann= 6 ,-1 , 0
       0      .1       0   32.29     .05       0  300.96     .06       0
   368.3    .045       0     389     .06       0  500.16      .1       0
Bank Sta=368.3,389
XS Rating Curve= 0 ,0
Exp/Cntr=0.3,0.1

Type RM Length L Ch R = 1 ,6164    ,250.8,248,244.8
XS GIS Cut Line= 3
2431449.25057308662425.4425180852431365.42397684662788.810439934
2431226.51410131663114.132256136
#Sta/Elev= 30
       0 1987.48    42.5 1974.52   104.1 1960.39   141.1 1950.99   160.1 1945.22
   165.7 1943.11   173.9 1938.96   182.1 1937.71   186.2 1936.32   235.5 1914.52
   272.4 1896.03   301.2 1877.36   366.8    1826   379.5 1814.45   392.6 1803.99
   414.3 1785.19     423 1782.03   458.8  1778.6   475.2  1777.7   481.6 1779.27
   488.3 1784.28   492.6 1786.47   523.1 1786.62   544.8 1791.57   575.2 1800.72
   614.4 1809.25   631.8 1813.67   688.3 1832.28   710.1  1840.9   726.6 1848.52
#Mann= 5 ,-1 , 0
       0      .1       0  430.99     .06       0   458.8    .045       0
   481.6     .06       0  545.95      .1       0
Bank Sta=458.8,481.6
XS Rating Curve= 0 ,0
Exp/Cntr=0.3,0.1

Type RM Length L Ch R = 1 ,5916    ,125.3,115.2,110.2
XS GIS Cut Line= 3
     2431165.773       662386.242431114.21346309662912.966665713
2431176.08247758663033.207586086
#Sta/Elev= 30
       0 1904.18    44.9 1893.57    97.1 1883.17   117.2 1877.84   157.1 1870.17
   185.5 1867.53   237.8 1865.66   277.9 1862.24     286  1860.5   291.4 1857.68
   298.1 1853.04   334.2  1824.1   362.1 1800.49   390.5 1779.43   398.5 1774.81
   402.4 1773.84     417 1773.23   430.7 1771.27   434.7 1771.65   438.9 1773.87
   446.8 1779.36   450.8 1780.49   464.6 1782.05     487  1782.6     491 1783.49
     499 1787.13   531.1  1790.7   580.9 1798.97   648.4 1815.86   664.5 1821.11
#Mann= 5 ,-1 , 0
       0      .1       0  392.57     .06       0     417    .045       0
   438.9     .06       0  493.28      .1       0
Bank Sta=417,438.9
XS Rating Curve= 0 ,0
Exp/Cntr=0.5,0.3

Type RM Length L Ch R = 1 ,5801    ,87.9,91.4,93.2
XS GIS Cut Line= 3
2431059.81336032662381.5824129562430993.75427045662710.392113909
2431126.30022129663053.301187471
#Sta/Elev= 30
       0 1859.33    42.1 1846.77    91.1 1836.79   120.9 1832.43     136 1830.96
   212.7  1828.4   282.8 1828.84   303.2 1827.92   314.6 1826.27   319.6 1824.58
   331.6 1817.12   348.8 1801.94   361.6 1788.22   370.2  1780.5   382.9 1771.26
   387.4 1768.91   400.2 1767.46   408.8 1767.69   416.9 1769.27   430.3 1774.36
   438.8  1776.3   460.3 1778.76     486 1779.72   507.5  1783.4   526.7 1788.75
   548.9 1791.16   567.5  1794.8   630.4  1815.3   661.3 1823.14     703 1837.52
#Mann= 7 ,-1 , 0
       0      .1       0   11.63      .1       0  267.32      .1       0
   323.4     .06       0   387.4    .045       0   416.9     .06       0
  523.53      .1       0
#XS Ineff= 2 , 0
          380.45  1773.6  426.05          1774.3
Permanent Ineff=
       F       F
Bank Sta=387.4,416.9
XS Rating Curve= 0 ,0
Exp/Cntr=0.5,0.3

Type RM Length L Ch R = 1 ,5709    ,66.3,70.2,63.8
XS GIS Cut Line= 3
     2431042.257      662357.0342430909.15751575662722.709091006
2431098.15096405663077.711337094
#Sta/Elev= 30
       0 1856.63    45.4 1840.71   142.4 1822.43   159.5 1821.03   200.8  1815.1
   265.9 1808.62   299.9 1806.21     317  1806.5   325.5 1805.61   338.3 1799.44
   350.6 1791.81   361.1 1780.17   372.3 1772.47   407.5 1771.22     412 1768.56
   421.1 1759.85   424.5 1757.55   430.1 1755.79   435.1 1755.39   443.6 1756.47
   445.31757.492   455.5 1765.29   460.6 1770.19   470.9 1775.44   507.2 1779.85
   552.5 1782.28   605.3 1799.39   647.9 1811.01   733.7 1841.48   791.3 1857.71
#Mann= 7 ,-1 , 0
       0      .1       0   43.23      .1       0  164.99      .1       0
   368.5     .06       0   424.5    .045       0   445.3     .06       0
  584.67      .1       0
Bank Sta=424.5,445.3
XS Rating Curve= 0 ,0
Exp/Cntr=0.5,0.3

Type RM Length L Ch R = 1 ,5639    ,433.7,445.2,466.4
XS GIS Cut Line= 3
     2431007.393      662339.777 2430843.5982605 662712.63762084
2431019.19609848 663081.64025714
#Sta/Elev= 30
       0 1847.75    38.4 1836.01    60.2 1831.82      82 1824.82   103.9 1820.26
   112.6 1820.17   182.5 1809.47   303.4 1795.33   315.5 1791.28   329.8 1782.38
   349.7 1773.75   374.8  1769.9   392.2 1770.26   420.3 1768.97   431.9 1764.52
   445.2 1754.03   449.6 1751.87     454 1751.42     473  1753.6   480.6 1757.52
   495.3 1771.77   511.6 1783.16   524.9 1785.62   551.5 1785.62   609.4 1801.46
     638 1806.12   675.2 1824.46   768.6 1856.61   796.2 1870.43   815.9 1878.76
#Mann= 7 ,-1 , 0
       0      .1       0    71.5      .1       0  187.21      .1       0
  302.92     .06       0   445.2    .045       0     473     .06       0
  519.05      .1       0
Bank Sta=445.2,473
XS Rating Curve= 0 ,0
Exp/Cntr=0.3,0.1