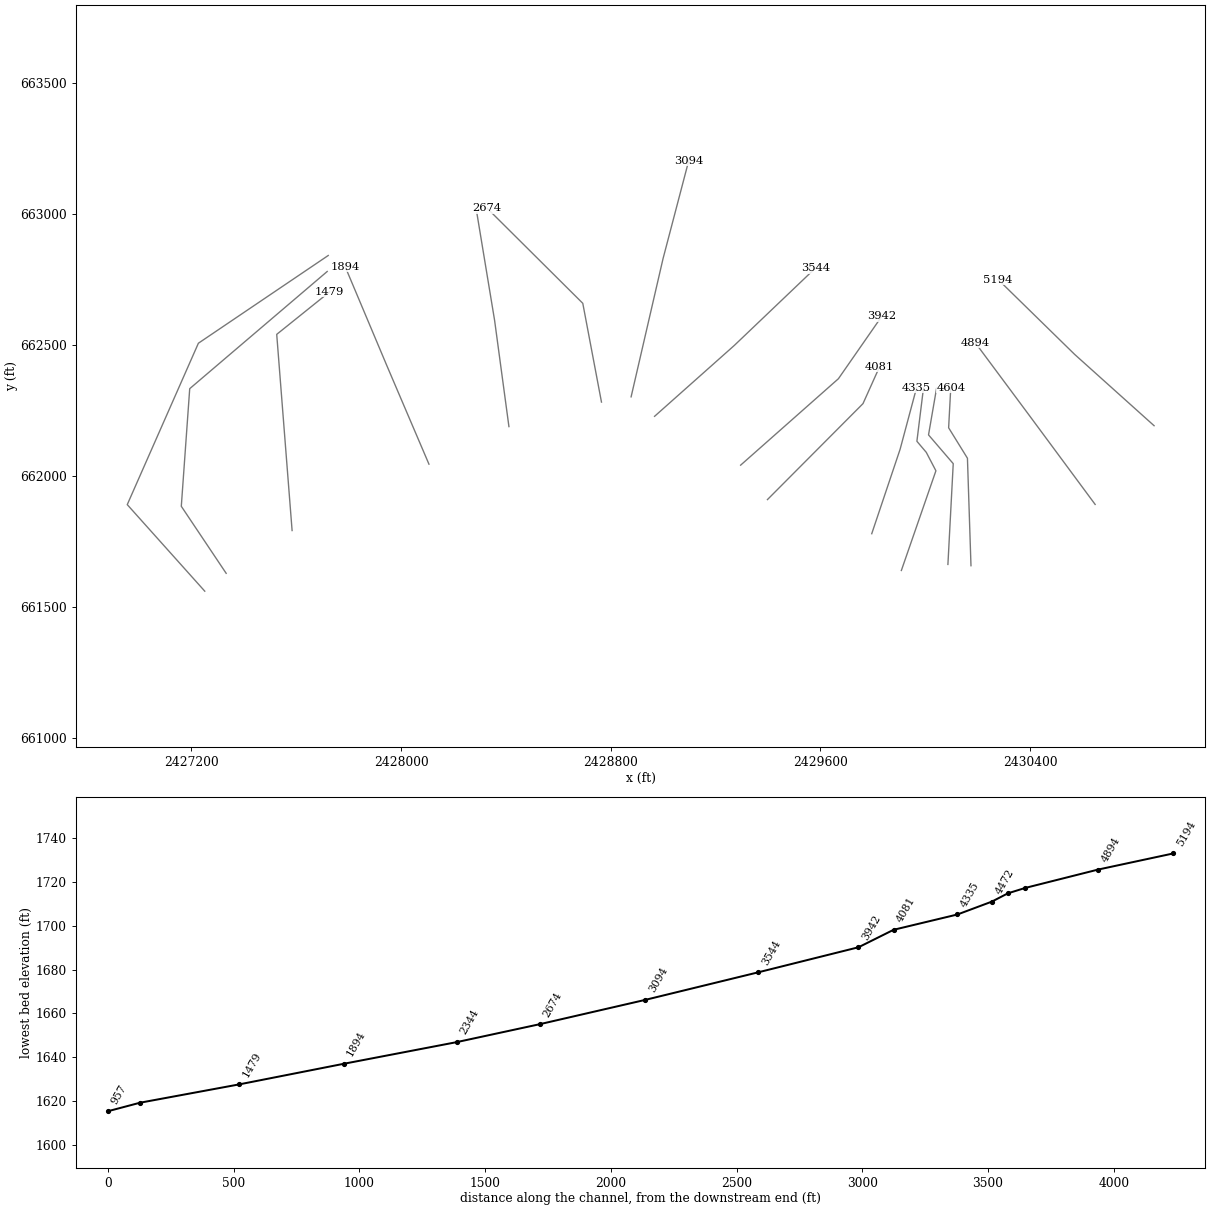
HEC-RAS study NFSBPOTMC_T1.prj: NFSBPOTMC_T1

--- NFSBPOTMC_T1.g01 (geometry) --- (continued)

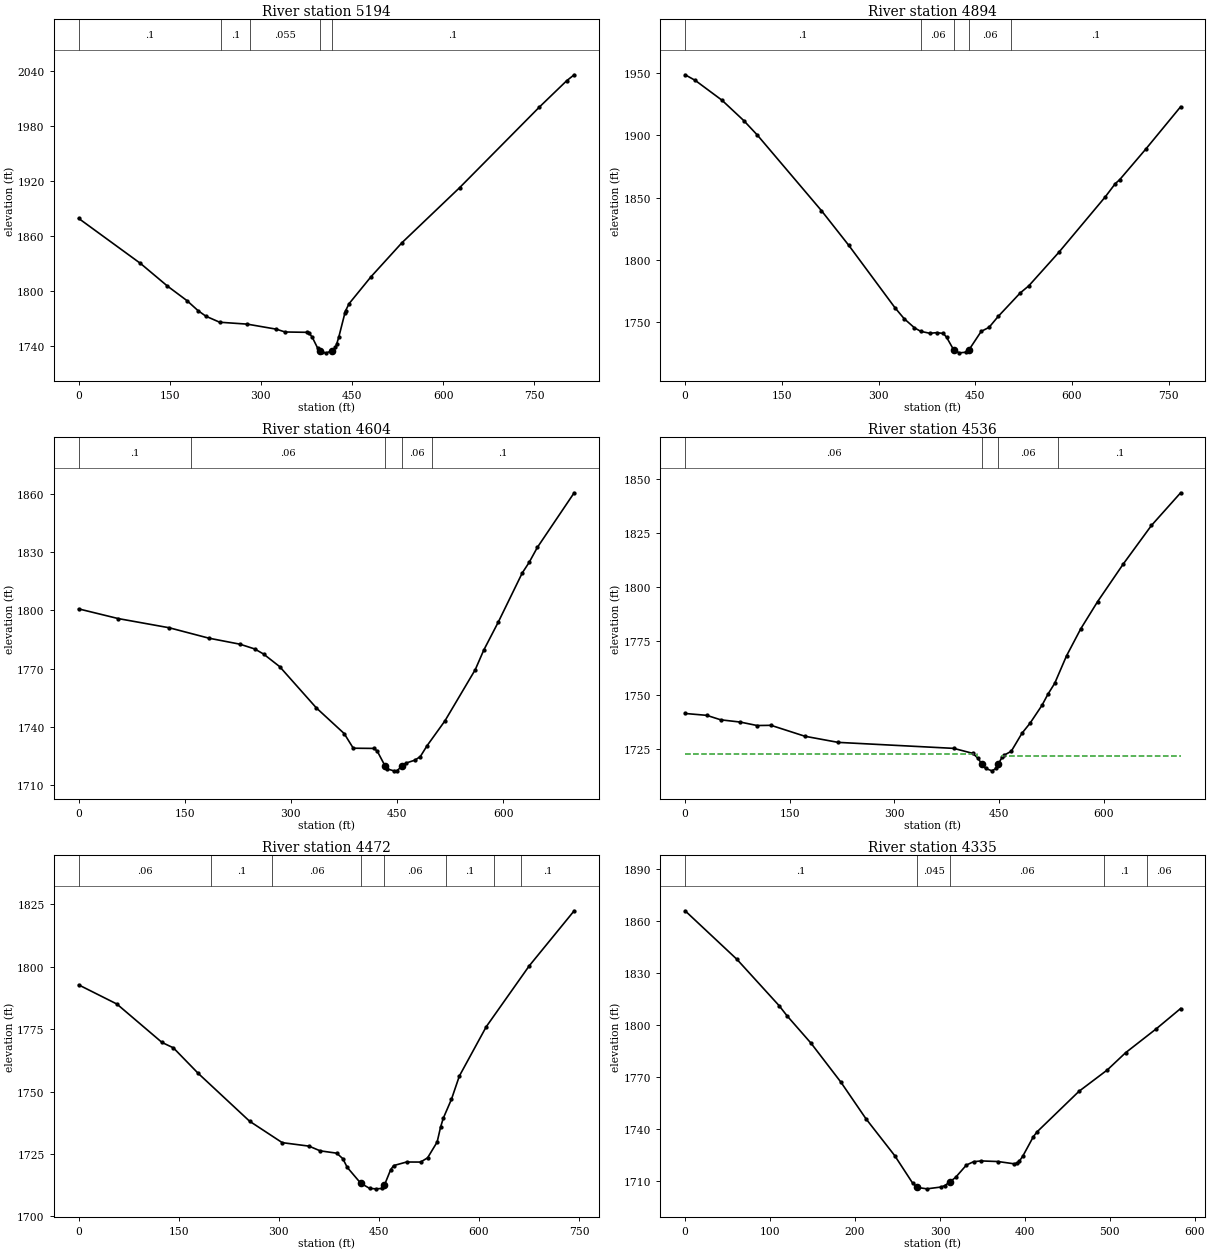
Type RM Length L Ch R = 1 ,5194    ,301,300,296.5
XS GIS Cut Line= 3
2430872.80227774662193.226024962     2430569.693      662465.351
     2430277.963       662750.79
#Sta/Elev= 30
       0 1879.74   101.8 1830.59   146.2 1805.88   178.3 1790.02   196.3 1779.25
   209.4 1773.04   232.1 1766.47   277.4 1764.39   325.3  1758.9   339.7 1755.83
   376.5 1755.45   379.4 1754.47   384.4 1750.19   393.5 1738.01   396.4 1735.24
   400.6 1733.49   407.7 1733.08   417.1  1735.3   422.7 1739.18   424.7 1742.71
   428.3 1750.67   438.1 1776.29   439.4 1779.06     445 1786.65   481.2 1816.11
   532.1  1853.2   626.9 1913.18   758.4 2001.25   803.2 2029.88   815.5 2036.36
#Mann= 5 ,-1 , 0
       0      .1       0  234.87      .1       0  282.15    .055       0
   396.4    .045       0   417.1      .1       0
Bank Sta=396.4,417.1
XS Rating Curve= 0 ,0
Exp/Cntr=0.3,0.1

Type RM Length L Ch R = 1 ,4894    ,289.8,289.8,288.3
XS GIS Cut Line= 3
 2430647.9402195661892.821304874     2430394.765      662235.147
2430190.32672504662510.295222858
#Sta/Elev= 30
       0 1948.21    15.5  1943.8    57.3 1927.81      91 1911.55     112 1899.99
   211.5 1839.48     254 1811.63   325.5 1761.79   339.8    1753   355.8  1745.7
   365.5 1742.88   379.8 1741.32   390.6 1741.88   400.6 1741.17   405.6 1738.12
     417  1727.7   425.6 1725.69   435.4 1726.18   439.9 1727.77   459.3 1742.88
   471.4 1746.06   485.6 1754.81   519.7 1773.57   533.1 1779.32   579.6 1806.07
   651.5 1850.38   667.3 1861.15     674 1864.23   714.4 1888.66   768.6 1922.64
#Mann= 5 ,-1 , 0
       0      .1       0  366.33     .06       0     417    .045       0
   439.9     .06       0  504.94      .1       0
Bank Sta=417,439.9
XS Rating Curve= 0 ,0
Exp/Cntr=0.3,0.1

Type RM Length L Ch R = 1 ,4604    ,69.2,68.6,72.9
XS GIS Cut Line= 4
2430174.20125417661658.9328716062430160.67879189662069.114227575
2430088.91826406 662185.266231552430097.11161658662338.498535626
#Sta/Elev= 30
       0 1800.79      56 1795.79     128 1791.06   184.1 1785.69   228.1 1782.58
   248.8 1780.14   261.3 1777.53   284.1 1771.04   336.1  1749.7   375.3 1736.53
   388.2 1728.96   417.2 1728.86   421.9 1727.57   433.51719.561     436 1718.34
   445.4  1717.3   450.1 1717.42   456.7 1719.61   462.5 1721.28     475 1722.77
   482.9 1724.63   492.4 1730.21   517.7 1743.04   560.6 1769.46   572.6 1779.53
   593.3  1794.1   627.1 1819.36   636.7 1824.71   648.3 1832.44   700.4 1860.64
#Mann= 5 ,-1 , 0
       0      .1       0  158.92     .06       0   433.5    .045       0
   456.7     .06       0  499.21      .1       0
Bank Sta=433.5,456.7
XS Rating Curve= 0 ,0
Exp/Cntr(USF)=0,0
Exp/Cntr=0.5,0.3

Type RM Length L Ch R = 1 ,4536    ,69.9,63.8,64.1
XS GIS Cut Line= 4
2430086.18658656661663.8519329722430106.48871971662048.398219554
2430012.21549093662158.1628922272430042.92793504662336.038288104
#Sta/Elev= 30
       0 1741.41    31.1 1740.54    51.1 1738.47    79.1 1737.43   103.2 1735.83
   123.2 1735.92   171.8 1730.86   219.3 1728.03   385.1 1725.25   412.2 1722.95
     420 1720.64   425.41717.862   430.6 1715.98   439.9 1714.85   446.1 1716.05
   448.91718.006   454.7 1721.34   456.9 1722.04   467.5  1723.9   482.9 1732.26
   494.5 1736.93   511.5 1745.15     520 1750.29   529.8 1755.38   546.7 1768.07
     567 1780.54   591.3 1793.22   627.9 1810.54   668.5 1828.48   710.3 1843.59
#Mann= 4 ,-1 , 0
       0     .06       0   425.4    .045       0   448.9     .06       0
  534.61      .1       0
#XS Ineff= 2 , 0
          418.07  1722.5  454.21          1721.6
Permanent Ineff=
       F       F
Bank Sta=425.4,448.9
XS Rating Curve= 0 ,0
Exp/Cntr(USF)=0,0
Exp/Cntr=0.5,0.3

Type RM Length L Ch R = 1 ,4472    ,150.6,136.8,121.4
XS GIS Cut Line= 5
2429908.56033428661640.7603257132430040.39209867662021.151513807
2430003.67749272 662091.471858812429967.83679694662133.819039501
2429993.09963933 662337.70311133
#Sta/Elev= 30
       0 1792.71    57.3 1785.04     125 1769.65     142  1767.5   179.4 1757.24
   256.3 1738.12   305.2 1729.55   345.2 1728.16   362.1 1726.27   386.9 1725.33
     396 1723.14   402.6 1719.67   422.8 1713.32   436.1 1711.25   445.2 1711.06
   454.2  1711.2   458.21712.428   467.7 1718.71   472.2 1720.37   491.6  1721.8
   512.6 1721.78   523.1 1723.48   537.4  1729.8   542.5 1735.71   546.5 1739.27
   558.9 1746.94   570.7 1756.22     611 1775.95   675.5 1800.34   742.8 1822.36
#Mann= 8 ,-1 , 0
       0     .06       0  198.89      .1       0  290.25     .06       0
   422.8    .045       0   458.2     .06       0  550.16      .1       0
   622.4     .06       0  663.24      .1       0
Bank Sta=422.8,458.2
XS Rating Curve= 0 ,0
Exp/Cntr=0.5,0.3

Type RM Length L Ch R = 1 ,4335    ,260.5,253.8,243.8
XS GIS Cut Line= 3
2429795.53026963661781.0591760232429903.88013719662103.611790994
2429966.70165305662338.418571393
#Sta/Elev= 30
       0 1866.04      61 1837.96   110.6 1811.19   120.1 1805.23   148.3 1789.39
   183.4  1766.9   212.9 1745.72   246.7 1724.43   267.8 1708.54   273.3 1706.01
   284.6 1705.19   301.5 1706.25   305.7 1707.07   311.6 1709.19   318.4 1711.81
   331.1 1718.94   339.5 1720.88   348.5 1721.34   368.5 1720.98   387.7 1719.64
     391 1720.21   393.3 1721.12   397.4 1724.01   409.9 1735.33   414.3 1738.16
   463.7 1761.63   496.9 1773.93   518.4 1783.88   554.8 1797.84   583.3  1809.5
#Mann= 5 ,-1 , 0
       0      .1       0   273.3    .045       0   311.6     .06       0
  492.52      .1       0  543.78     .06       0
Bank Sta=273.3,311.6
XS Rating Curve= 0 ,0
Exp/Cntr=0.3,0.1

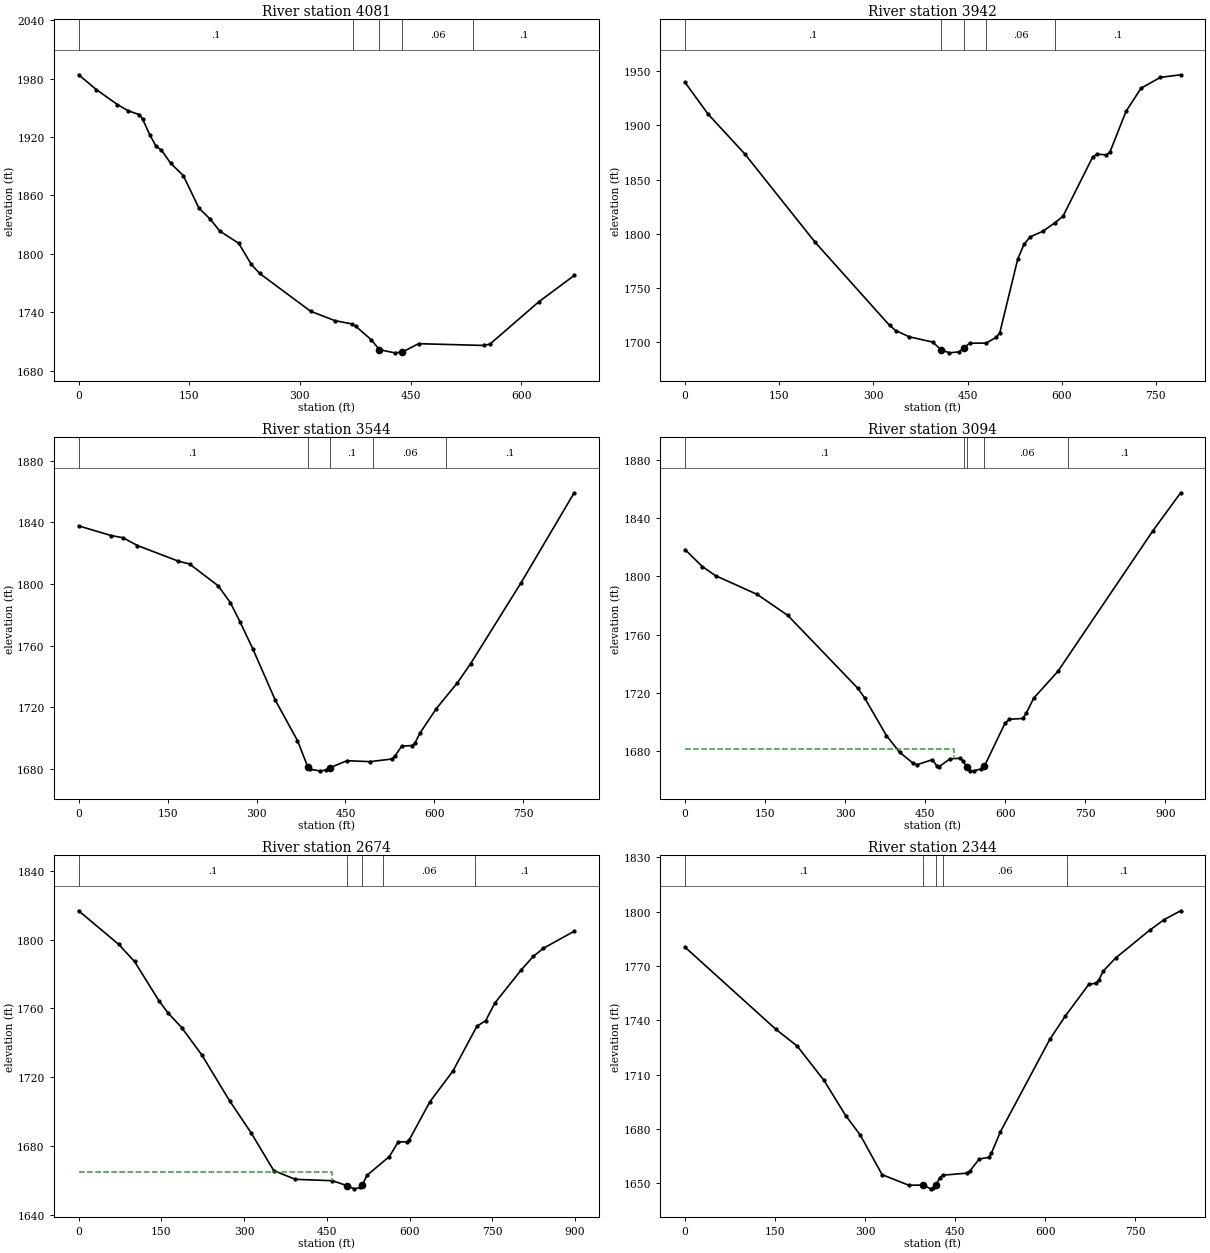
Type RM Length L Ch R = 1 ,4081    ,140.7,139.6,138.6
XS GIS Cut Line= 3
2429397.63874827661911.3141211812429762.18396438662277.488639402
2429825.75981016662418.932960194
#Sta/Elev= 30
       0 1983.85    24.2 1968.53    52.6 1953.28    67.1 1946.89    82.5 1942.85
    86.6 1938.47    96.6 1921.97   105.1 1910.25   112.3 1906.47   124.9 1892.82
   141.9 1880.34   163.1 1846.87   178.7 1835.27   191.3 1823.29     217 1810.78
     234 1789.15   245.4 1779.78   314.4 1740.96   347.4 1731.28   370.1 1727.93
   375.8 1725.45   396.5 1711.74   407.8 1701.49   428.4  1698.2   438.71698.917
   460.8 1707.61   548.9 1705.78   557.7  1707.2   623.5 1750.41   671.8 1777.66
#Mann= 5 ,-1 , 0
       0      .1       0  371.72     .06       0   407.8    .045       0
   438.7     .06       0  535.27      .1       0
Bank Sta=407.8,438.7
XS Rating Curve= 0 ,0
Exp/Cntr=0.3,0.1

Type RM Length L Ch R = 1 ,3942    ,397.3,397.7,395.6
XS GIS Cut Line= 3
2429295.28684686662042.6636724812429668.45841073662372.568968078
2429834.76312941662611.885514474
#Sta/Elev= 30
       0 1939.48    36.6 1910.31    95.4 1873.42   206.6 1792.55   325.7 1715.54
   335.6  1710.8   356.8 1705.06   394.4 1700.13   407.8 1693.07   421.1 1690.22
   436.2 1691.09   444.7 1695.06   453.2 1699.09   479.8 1699.22   495.8 1704.61
   501.4  1708.8   530.1 1776.97   539.9 1790.15   549.6 1797.08   570.4 1802.44
   588.6 1809.89     602  1816.1   649.3 1870.69   656.3 1873.44     671 1872.72
   676.7 1875.14   702.6 1912.98   726.4 1934.17   757.2 1944.19   789.5 1946.58
#Mann= 5 ,-1 , 0
       0      .1       0   407.8    .045       0   444.7      .1       0
   479.8     .06       0   588.6      .1       0
Bank Sta=407.8,444.7
XS Rating Curve= 0 ,0
Exp/Cntr(USF)=0,0
Exp/Cntr=0.3,0.1

Type RM Length L Ch R = 1 ,3544    ,441.2,450,459.8
XS GIS Cut Line= 3
     2428966.954      662229.009     2429270.767      662499.143
2429581.26624538662795.271631933
#Sta/Elev= 30
       0 1837.71      55 1831.39    74.7 1830.03    99.1 1824.96   168.3 1814.79
   187.1 1812.95   235.2 1798.87   255.7 1787.99   272.7 1775.04   294.1  1757.6
   331.6 1724.65     369 1698.47   386.5 1681.29   390.5 1679.82   406.2 1678.81
   417.7 1679.19   423.1 1680.68   452.5  1685.4   491.2 1684.77     528 1686.47
   533.7 1688.52   544.7 1694.81     562 1695.22   566.8 1696.64   576.1 1703.62
   603.2  1719.2   638.7 1735.91     661 1748.35   745.9 1800.71   835.6 1859.16
#Mann= 5 ,-1 , 0
       0      .1       0   386.5    .045       0   423.1      .1       0
  497.18     .06       0  620.16      .1       0
Bank Sta=386.5,423.1
XS Rating Curve= 0 ,0
Exp/Cntr=0.3,0.1

Type RM Length L Ch R = 1 ,3094    ,405.9,419.8,436.9
XS GIS Cut Line= 3
     2428877.411      662303.327     2428999.352      662831.149
2429097.45844255663205.123912881
#Sta/Elev= 30
       0 1818.48    32.4 1806.75      57 1800.52     135 1787.63   192.5 1773.14
   323.9 1722.93   336.2 1716.49   377.2 1690.46   401.9 1678.97   427.6 1671.33
   434.7 1670.44   463.5  1673.9   471.7 1669.47   475.8 1669.08   496.3 1674.45
   514.3 1674.83     521 1673.12   527.7 1668.52   533.2 1666.37     541  1666.2
   554.1 1667.52   560.7 1669.39   599.4 1698.97   607.6 1701.67   632.7 1702.26
   639.3 1705.95   653.1 1716.21   698.3 1734.59   876.4  1831.4   928.4 1857.57
#Mann= 5 ,-1 , 0
       0      .1       0  522.23     .06       0   527.7    .045       0
   560.7     .06       0  718.28      .1       0
#XS Ineff= 2 , 0
          504.04 1681.16
Permanent Ineff=
       F       F
Bank Sta=527.7,560.7
XS Rating Curve= 0 ,0
Exp/Cntr=0.3,0.1

Type RM Length L Ch R = 1 ,2674    ,336.8,330.2,321.1
XS GIS Cut Line= 3
     2428764.338      662283.379 2428693.0335998662660.234085829
     2428328.022      663023.163
#Sta/Elev= 30
       0 1816.76    72.8 1797.17   101.3 1787.28   146.1 1764.18   162.3 1757.26
   186.8 1748.86   223.4 1732.88   273.5 1706.37     313 1687.48   353.7 1665.69
   392.7 1660.62   460.1 1659.82     486 1656.97   499.6 1655.09   510.9 1655.88
   514.3 1657.56   522.8 1662.96   563.2 1673.84   579.4 1682.39   595.5 1682.45
   599.2 1683.48   636.9 1705.78   678.4 1723.53     722 1749.62   737.8 1752.85
   754.7 1763.21   802.8 1782.58   824.1 1790.19   842.4 1794.94   898.3 1804.86
#Mann= 5 ,-1 , 0
       0      .1       0     486    .045       0   514.3      .1       0
  551.85     .06       0  717.77      .1       0
#XS Ineff= 2 , 0
          459.87 1664.64
Permanent Ineff=
       F       F
Bank Sta=486,514.3
XS Rating Curve= 0 ,0
Exp/Cntr=0.3,0.1

Type RM Length L Ch R = 1 ,2344    ,446.8,450,451.6
XS GIS Cut Line= 3
     2428411.222      662189.768     2428356.522      662595.372
2428288.70935367663005.808629085
#Sta/Elev= 30
       0  1780.3   150.8 1735.11   186.8  1725.7   231.2 1706.83   267.5 1687.32
   291.7 1676.63   328.1 1654.72   372.5 1648.89   396.7 1648.98   408.8  1646.9
   412.8 1647.19     4181649.291   424.3 1653.07   429.1 1654.43   469.3 1655.58
   473.7  1656.5   489.9 1663.38   506.1 1664.28   510.1 1666.53   525.2 1678.45
   607.4 1729.44   633.1 1742.26   672.3 1759.77   684.5 1760.44   688.8 1762.07
   696.6 1767.21   716.9 1774.31   773.7 1789.71     798 1795.57   825.3 1800.43
#Mann= 5 ,-1 , 0
       0      .1       0   396.7    .045       0     418      .1       0
  429.94     .06       0   635.3      .1       0
Bank Sta=396.7,418
XS Rating Curve= 0 ,0
Exp/Cntr=0.3,0.1

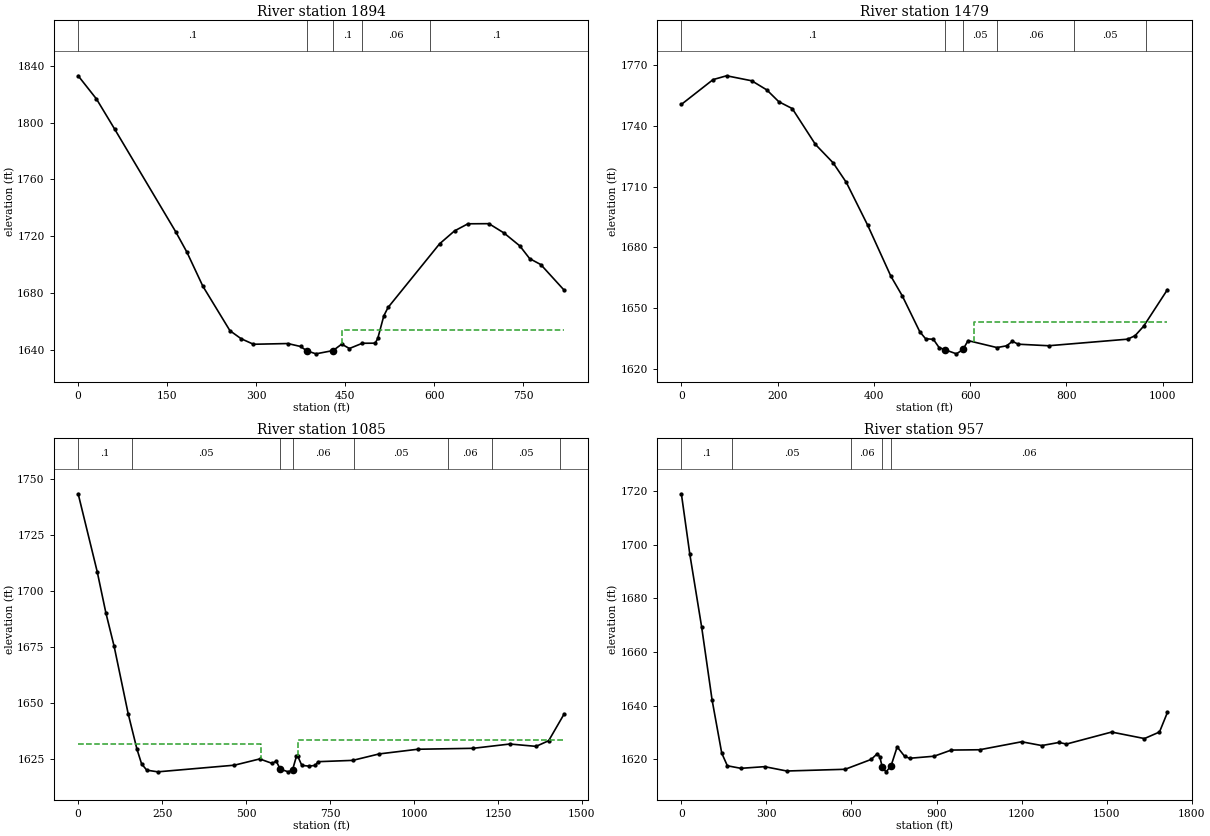
Type RM Length L Ch R = 1 ,1894    ,422,414.5,407.9
XS GIS Cut Line= 3
     2428106.071      662046.449     2427945.167      662423.011
      2427786.26      662800.429
#Sta/Elev= 30
       0 1832.98    30.9  1816.6    61.4 1795.48   164.4 1723.03   183.2 1708.71
   210.1 1684.69   255.8 1653.29   274.5 1647.68   295.4 1643.74   353.3 1644.25
   374.7 1642.18   385.1 1639.18   400.7 1636.99   429.6 1639.31   444.1 1643.82
   457.1 1640.75   478.8 1644.44   500.5 1644.51   504.9 1647.89   515.1 1663.82
   522.2 1669.66     609 1714.52   634.2 1723.64   656.8 1728.65   692.2 1728.74
   717.5  1722.2   744.2 1713.09   760.9 1704.08   779.6 1699.91     819 1681.84
#Mann= 5 ,-1 , 0
       0      .1       0   385.1    .045       0   429.6      .1       0
  477.67     .06       0  592.27      .1       0
#XS Ineff= 2 , 0
                          444.47         1653.87
Permanent Ineff=
       F       F
Bank Sta=385.1,429.6
XS Rating Curve= 0 ,0
Exp/Cntr=0.3,0.1

Type RM Length L Ch R = 1 ,1479    ,395.7,394.8,391.5
XS GIS Cut Line= 3
2427583.89082351661793.1516108152427525.23078477662541.748066673
2427727.07334801662703.890251012
#Sta/Elev= 30
       0 1750.49    65.9 1762.72      94  1764.6   146.2 1762.13   177.6 1757.62
   202.4 1751.83   230.4 1748.44   278.6 1730.76   315.2 1721.74   342.8 1712.03
   386.9 1691.06   435.1 1665.94   459.1 1656.12   495.3 1638.52   507.3 1635.07
   523.6 1634.75   535.4 1630.72   547.4 1629.65   571.5 1627.61   585.11629.753
   595.6 1634.13   655.7  1630.7   675.8 1631.57   687.8 1633.79   699.9 1632.36
   763.1  1631.6   927.3 1634.84   942.7 1636.56   960.5 1641.24  1009.8 1659.21
#Mann= 6 ,-1 , 0
       0      .1       0   547.4    .045       0   585.1     .05       0
  655.98     .06       0  816.61     .05       0  964.99      .1       0
#XS Ineff= 2 , 0
                          608.62         1643.49
Permanent Ineff=
       F       F
Bank Sta=547.4,585.1
XS Rating Curve= 0 ,0
Exp/Cntr=0.3,0.1

Type RM Length L Ch R = 1 ,1085    ,126.4,127.8,126.1
XS GIS Cut Line= 4
 2427332.3335716661629.8934484392427161.15769124661885.714218442
2427193.26648985662334.5406875592427717.85323074662781.685801067
#Sta/Elev= 30
       0 1743.19    56.6 1708.54    82.6 1690.06   107.1  1675.2   148.9 1645.15
   174.9 1629.43   188.9 1622.77   204.3 1619.98     237 1619.23   465.4  1622.2
   540.6 1624.98   577.7 1622.99   589.7 1624.02   601.7 1620.43   625.8 1619.23
   638.41620.137   649.9 1626.16   653.9 1626.17   665.9 1622.12   685.9 1621.79
     706 1622.08   714.6 1623.76   817.5 1624.34   896.4 1627.22  1011.1  1629.3
  1176.2 1629.72  1285.3 1631.63  1363.4 1630.59  1400.9  1633.1  1447.1 1645.06
#Mann= 8 ,-1 , 0
       0      .1       0  161.55     .05       0   601.7    .045       0
   638.4     .06       0  820.44     .05       0 1102.03     .06       0
 1230.73     .05       0 1434.05      .1       0
#XS Ineff= 2 , 0
          543.74 1631.82  653.75         1633.54
Permanent Ineff=
       F       F
Bank Sta=601.7,638.4
XS Rating Curve= 0 ,0
Exp/Cntr=0.5,0.3

Type RM Length L Ch R = 1 ,957     ,53.5,54.1,54.8
XS GIS Cut Line= 4
 2427250.6989667661561.7407360782426954.94777062661892.052057896
2427226.35260964662507.9281925122427721.81399517662842.758029861
#Sta/Elev= 30
       0 1718.93    29.9 1696.33    71.6 1669.24   108.4 1642.07   142.4  1622.3
   162.2  1617.6   209.8 1616.65   293.8 1617.27   371.7 1615.65   577.6 1616.29
   669.4 1619.96   691.3 1622.12     700 1620.91   708.7 1617.04   721.9 1615.34
   739.3 1617.47   761.2 1624.64   787.4 1621.14   804.9 1620.39   891.4 1621.16
   952.1 1623.45  1052.2 1623.57  1200.3 1626.54  1271.4 1625.13    1332 1626.29
  1358.3 1625.69  1517.6 1630.16  1633.4 1627.74  1686.5 1630.18  1714.4 1637.45
#Mann= 5 ,-1 , 0
       0      .1       0  179.78     .05       0  598.29     .06       0
   708.7    .045       0   739.3     .06       0
#XS Ineff= 2 ,-1
    3.15   688.41620.863  769.01 1588.831620.746
Permanent Ineff=
       F       F
Bank Sta=708.7,739.3
XS Rating Curve= 0 ,0
Exp/Cntr=0.5,0.3