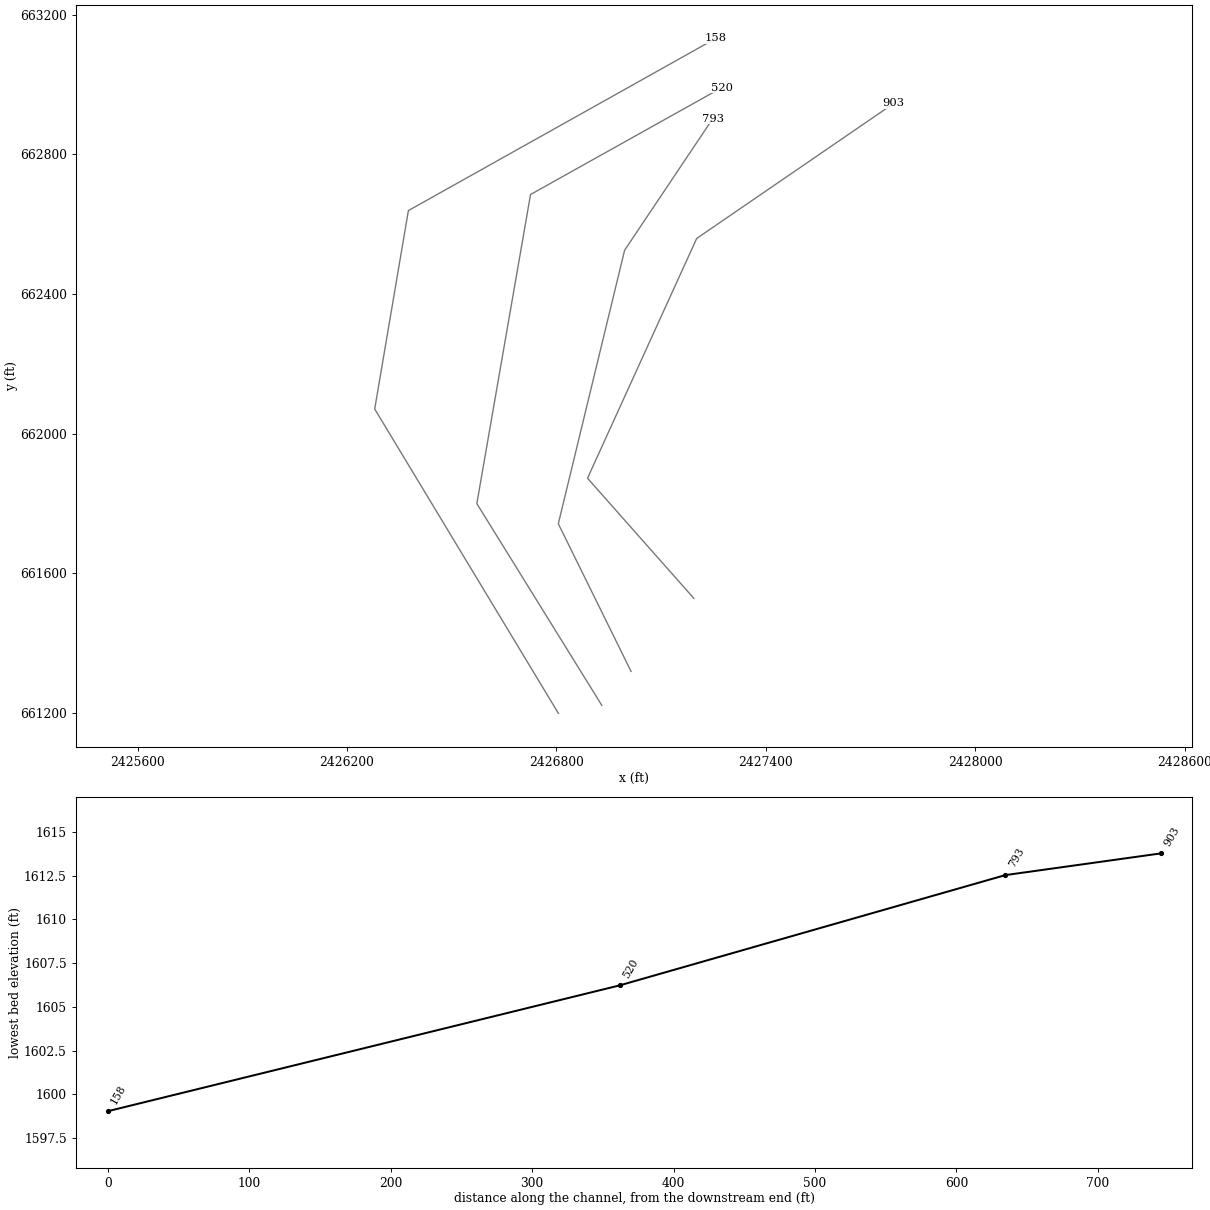
HEC-RAS study NFSBPOTMC_T1.prj: NFSBPOTMC_T1

--- NFSBPOTMC_T1.g01 (geometry) --- (continued)

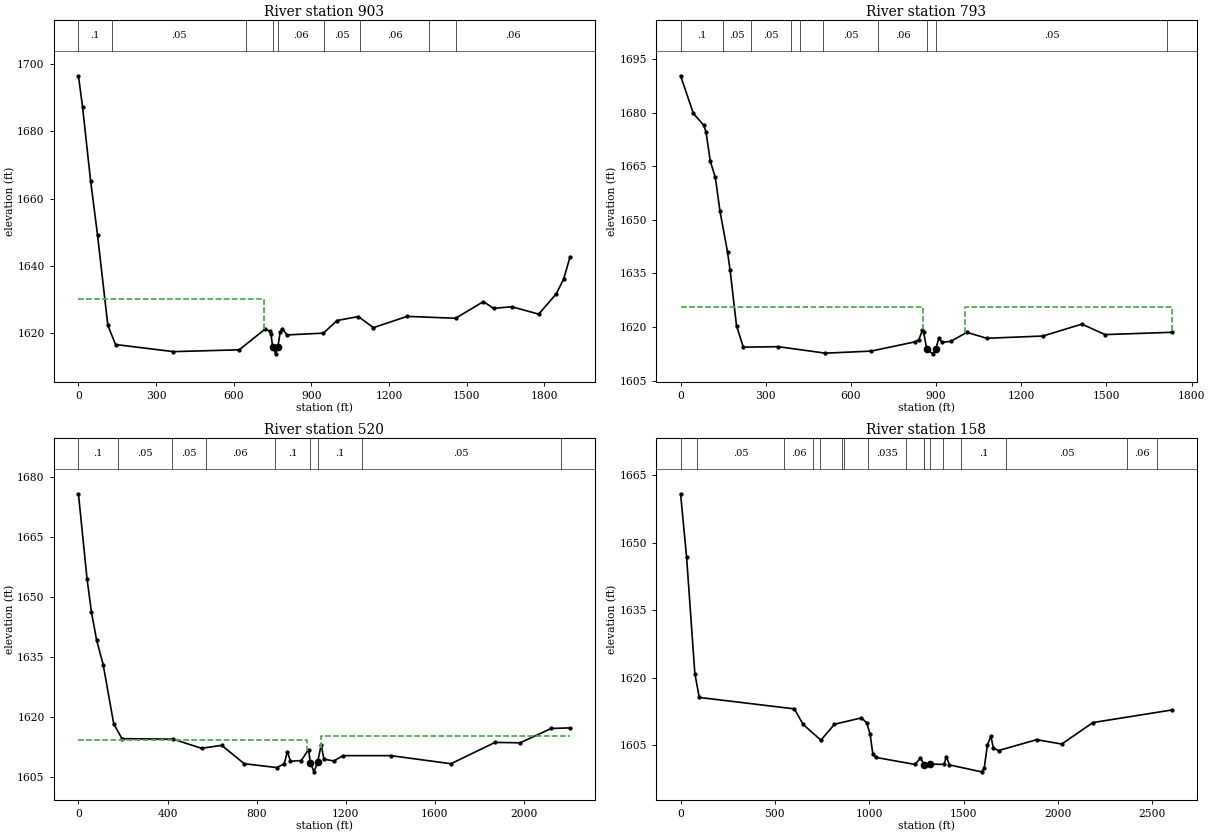
Type RM Length L Ch R = 1 ,903     ,111.6,109.9,112
XS GIS Cut Line= 4
2427193.99634645661527.7339555212426889.28259025661872.036415771
2427202.11658368662559.0931362062427766.69051353662945.994569469
#Sta/Elev= 30
       0 1696.57    15.9 1687.31    46.9 1665.38    73.7 1649.18   113.5 1622.29
   143.4 1616.54     367 1614.43   621.1 1614.97   722.2  1621.2   739.8 1620.46
   744.2 1619.57   749.81615.951   761.8 1613.77   770.11615.696   779.4 1620.21
   788.2 1621.19   805.7  1619.4   946.4 1619.94   999.1 1623.69  1081.1 1624.86
  1139.8 1621.57  1269.7 1624.93  1456.7 1624.36  1564.6 1629.33  1603.5 1627.31
  1674.3 1627.79    1778 1625.59  1845.9 1631.63  1874.9 1636.16  1899.1 1642.66
#Mann= 9 ,-1 , 0
       0      .1       0   129.5     .05       0  646.24     .06       0
   749.8    .045       0   770.1     .06       0  950.43     .05       0
 1086.48     .06       0 1356.01     .05       0 1458.53     .06       0
#XS Ineff= 2 , 0
          718.46 1630.24
Permanent Ineff=
       F       F
Bank Sta=749.8,770.1
XS Rating Curve= 0 ,0
Exp/Cntr=0.5,0.3

Type RM Length L Ch R = 1 ,793     ,270,272.6,272.4
XS GIS Cut Line= 4
2427014.09646487 661318.39916572     2426805.563 661741.52991698
2426995.58433406 662525.309720862427247.82773378662901.827077979
#Sta/Elev= 30
       0 1690.29    45.1 1679.75    80.8 1676.52    89.5 1674.69   104.4 1666.47
   122.4 1661.86   138.8 1652.42   165.5 1640.94   174.5 1635.85     197 1620.41
   220.9  1614.4   343.9 1614.53     510 1612.72   670.7 1613.29   827.1 1615.91
   839.4 1616.51   851.8 1619.21   855.9 1618.64   867.2 1613.82   888.8 1612.53
   898.61613.819   909.4 1616.84   921.8 1615.73   952.1 1616.05  1008.2 1618.54
  1078.2 1616.88  1276.1 1617.51  1413.3 1620.84    1495 1617.91  1731.4 1618.56
#Mann= 10 ,-1 , 0
       0      .1       0  149.12     .05       0  248.02     .05       0
  387.46     .05       0  419.28     .05       0  500.39     .05       0
  696.15     .06       0   867.2    .045       0   898.6     .05       0
 1714.39     .06       0
#XS Ineff= 2 , 0
           853.8 1625.65 1002.01          1625.6
Permanent Ineff=
       F       F
Bank Sta=867.2,898.6
XS Rating Curve= 0 ,0
Exp/Cntr=0.3,0.1

Type RM Length L Ch R = 1 ,520     ,365.7,361.9,365
XS GIS Cut Line= 4
2426930.16592027661221.2671573032426572.10433781 661799.22546957
2426726.02825292662685.0229828122427273.87027337662991.149537895
#Sta/Elev= 30
       0 1675.76    38.5 1654.53    58.4 1646.17    81.9 1639.09   111.2 1632.99
   158.4 1618.23   195.4 1614.52   425.4  1614.4   552.4 1612.12   642.9 1612.86
   744.5 1608.26   889.4  1607.3   923.1 1608.18   937.8 1611.27   951.6 1608.88
  1000.3 1609.05  1032.8  1611.8  1040.9 1608.54  1057.1 1606.23  1073.4  1608.6
  1089.6 1612.98  1101.8 1609.41  1146.4 1608.94  1186.9 1610.28  1402.2 1610.28
    1672 1608.26  1869.8 1613.59    1983 1613.49  2121.7 1617.08  2206.5 1617.22
#Mann= 9 ,-1 , 0
       0      .1       0   175.7     .05       0  419.51     .05       0
  570.93     .06       0  882.39      .1       0  1040.9    .045       0
  1073.4      .1       0  1272.6     .05       0 2164.12     .06       0
#XS Ineff= 2 , 0
         1027.22  1614.2 1086.78         1615.09
Permanent Ineff=
       F       F
Bank Sta=1040.9,1073.4
XS Rating Curve= 0 ,0
Exp/Cntr=0.3,0.1

Type RM Length L Ch R = 1 ,158     ,,,
XS GIS Cut Line= 4
2426805.90856239661198.1455300532426279.44821082662070.401754005
2426376.01297759 662638.937777442427257.34719905663132.529471471
#Sta/Elev= 30
       0 1660.88      32 1646.74    75.7 1620.88      99 1615.59     603 1613.04
   649.7 1609.57   743.7 1606.08   815.7 1609.62   958.3 1611.04   986.7 1609.95
  1004.7 1607.37  1018.8 1603.06  1035.5 1602.25  1242.5 1600.68  1270.9 1602.07
  1292.6 1600.63  1323.3 1600.78  1396.7 1600.69  1408.8 1602.45    1425 1600.58
  1595.4 1599.04  1609.2 1599.79  1626.1 1604.98  1644.5 1606.97  1658.2 1604.31
  1685.6 1603.78  1887.5 1606.19  2020.4 1605.22  2185.5    1610  2605.6 1612.81
#Mann= 17 ,-1 , 0
       0      .1       0   87.92     .05       0  548.36     .06       0
  701.84      .1       0  737.56     .05       0  855.32     .06       0
  864.78    .055       0     992    .035       0 1193.35     .02       0
  1290.9    .035       0  1292.6    .045       0  1323.3    .035       0
 1388.44      .1       0 1485.99      .1       0 1725.08     .05       0
 2366.77     .06       0 2524.91     .05       0
Bank Sta=1292.6,1323.3
XS Rating Curve= 0 ,0
Exp/Cntr=0.3,0.1
LCMann Table=0

Chan Stop Cuts=-1
Use User Specified Reach Order=0
Composite Channel Slope=5